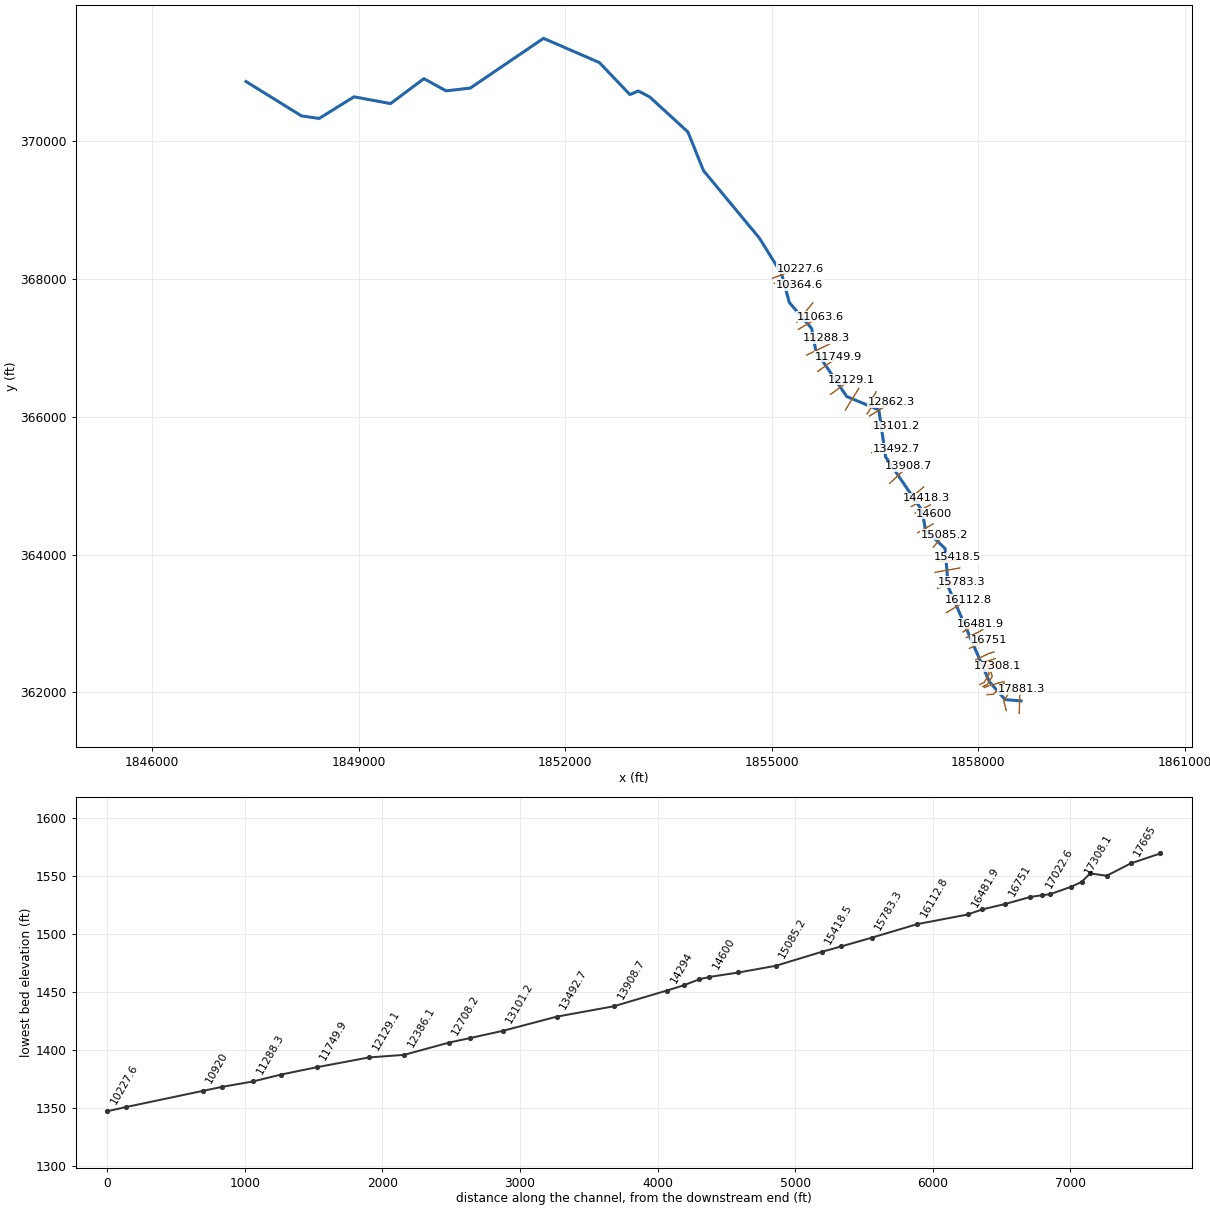
--- CABINCK.prj (project) ---

Proj Title=CABINCK
Current Plan=p01
Default Exp/Contr=0,0
English Units
Geom File=g01
Flow File=f01
Plan File=p01
BEGIN DESCRIPTION:
END DESCRIPTION:
DSS Export Rating Curves= 0
DSS Export Rating Curve Sorted= 0
DSS Export Volume Flow Curves= 0
DXF OffsetX= 0
DXF OffsetY= 0
DXF ScaleX= 0
DXF ScaleY= 0

--- CABINCK.p01 (plan) ---

Plan Title=Floodplain
Program Version=4.00
Geom File=g01
Flow File=f01
K Sum by GR=0
Std Step Tol=0.01
Critical Tol=0.01
Num of Std Step Trials=20
Max Error Tol=0.3
Flow Tol Ratio=0.001
Split Flow NTrial=30
Split Flow Tol=0.02
Split Flow Ratio=0.02
Log Output Level=0
Friction Slope Method=1
Unsteady Friction Slope Method=2
Unsteady Bridges Friction Slope Method=1
Global Log Level=0
CheckData=False
Run HTab=0
Run UNet=0
Run PostProcess=0
UNET Theta=0
UNET Theta Warmup=0
UNET ZTol=0
UNET ZSATol=0
UNET MxIter=0
UNET MaxInSteps=0
UNET DtIC=0
UNET DtMin=0
UNET MaxCRTS=0
UNET WFStab=0
UNET SFStab=0
UNET WFX=0
UNET SFX=0
UNET DSS MLevel=0
UNET DZMax Abort=0
UNET Convert EG Bridges=0
UNET Use Existing IB Tables=0
UNET Froude Limit=0
UNET Froude Power=0
Write IC File=0
Echo Input=False
Echo Output=False
Write Detailed=0

--- CABINCK.f01 (steady flow) ---

Flow Title=NFF Regression Equation
Program Version=4.10
Number of Profiles= 1
Profile Names=P100yr
River Rch & RM=CABINCK,Main            ,17881.3
647.1305
River Rch & RM=CABINCK,Main            ,17077.1
1062.478
River Rch & RM=CABINCK,Main            ,15783.3
1104.462
River Rch & RM=CABINCK,Main            ,13101.2
 1208.91
River Rch & RM=CABINCK,Main            ,9845.2
1339.535
River Rch & RM=CABINCK,Main            ,7749.6
1488.198
River Rch & RM=CABINCK,Main            ,5043.4
1640.682
River Rch & RM=CABINCK,Main            ,449.4
1809.755
Boundary for River Rch & Prof#=CABINCK,Main            , 1
Up Type= 0
Dn Type= 3
Dn Slope=0.018
DSS Import GetInterval= 0
DSS Import GetPeak= 0
DSS Import FillOption= 0

--- CABINCK.g01 (geometry) ---

Geom Title=USGS 10m DEM
Program Version=4.10

River Reach=CABINCK         ,Main
Reach XY= 30
     1858619.513      361874.114     1858387.723      361894.142
      1858159.48      362154.814     1857564.268      363528.086
     1857516.603      364088.073     1857231.522      364359.105
     1857185.171      364636.688     1856654.026      365416.892
     1856555.048      366101.565       1856088.8      366295.106
     1855639.937      366957.108      1855580.12      367282.953
      1855254.68       367660.82     1855142.238      368077.186
     1854820.027      368596.238     1854009.023      369575.032
     1853783.103      370135.969     1853226.685       370646.38
     1853062.574      370732.322     1852939.802      370679.877
     1852497.135      371144.603     1851685.645      371496.593
     1850622.955      370774.508     1850269.979      370733.615
     1849948.657       370911.31     1849464.276      370549.011
     1848933.234       370647.17     1848428.601      370333.724
     1848172.321      370369.461     1847365.502      370869.213

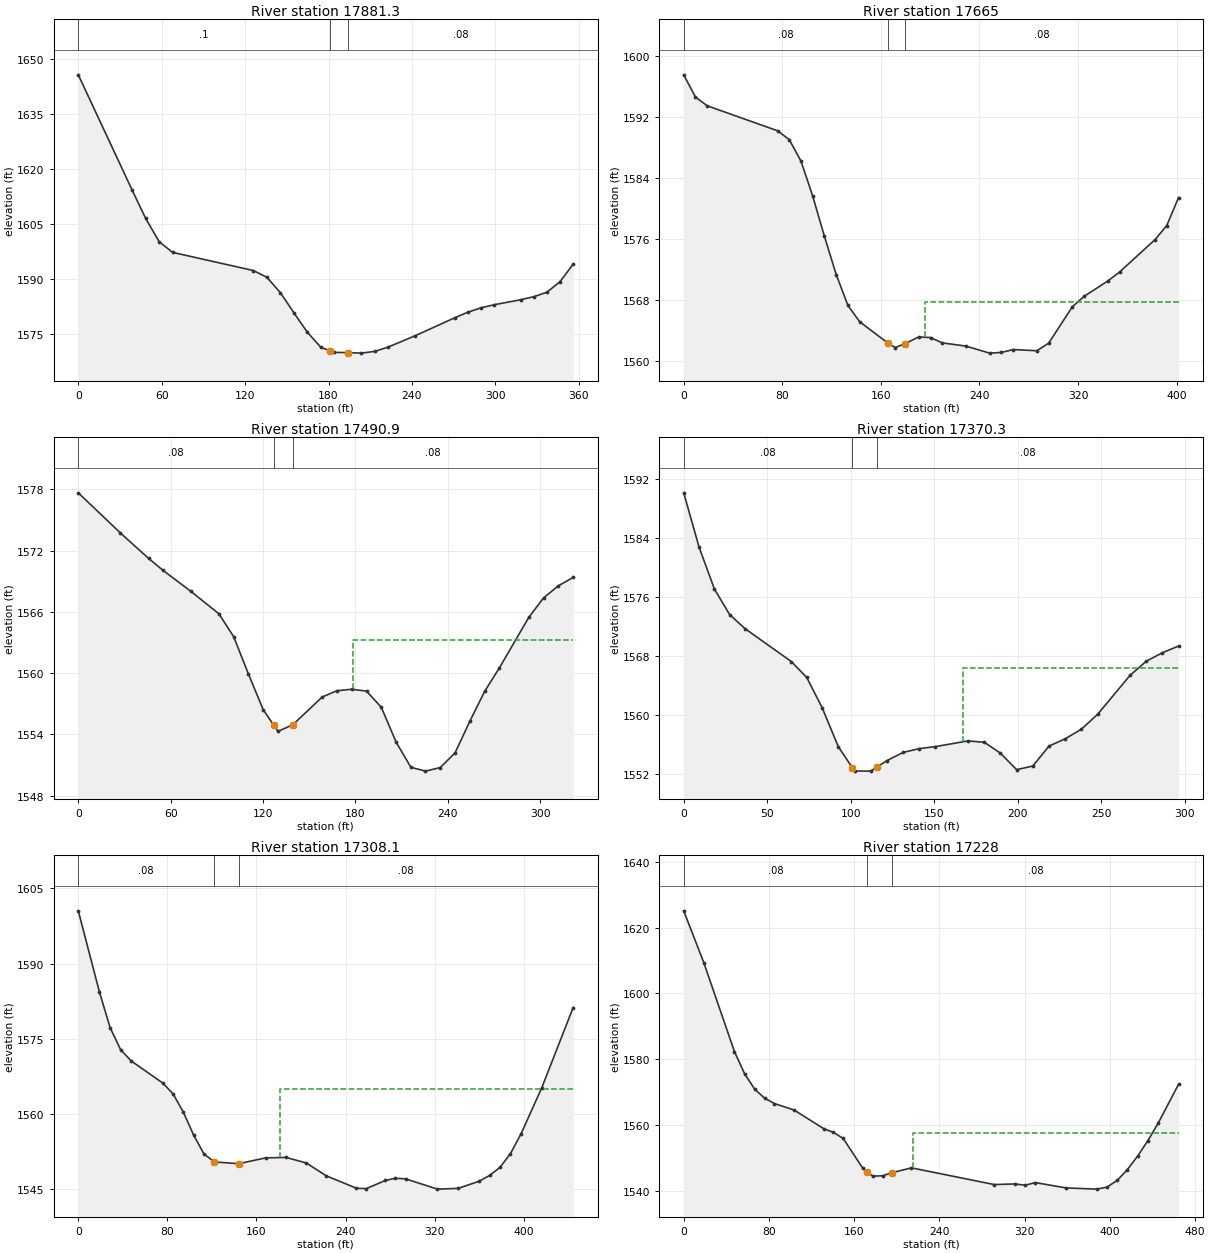
Type RM Length L Ch R = 1 ,17881.3 ,228.8,216.3,203.7
XS GIS Cut Line= 3
     1858594.523      361693.693     1858600.355      361945.679
     1858629.234      362045.552
#Sta/Elev= 27
       0 1645.73    38.8 1614.19    48.5 1606.48    58.2 1600.12    67.9 1597.22
     126 1592.26   135.7 1590.41   145.4 1586.22   155.1 1580.72   164.8  1575.4
   174.5  1571.3   180.91570.375   184.2  1569.9   193.9 1569.84   203.6  1569.7
   213.3 1570.18     223 1571.37   242.4 1574.46     271 1579.39   280.4  1580.9
   289.9  1582.1   299.3 1582.93   318.2 1584.28   327.7 1585.13   337.1 1586.32
   346.6 1589.24     356    1594
#Mann= 3 , 0 , 0
       0      .1       0   180.9    .045       0   193.9     .08       0
Bank Sta=180.9,193.9
XS Rating Curve= 0 ,0
Exp/Cntr=0.3,0.1

Type RM Length L Ch R = 1 ,17665   ,178.9,174.1,168.6
XS GIS Cut Line= 3
     1858406.002      361734.025     1858369.534      361872.091
     1858504.998      362092.644
#Sta/Elev= 30
       0 1597.49     9.5 1594.59      19 1593.44    76.2 1590.16    85.7 1588.99
    95.2 1586.18   104.7  1581.6   114.2 1576.34   123.8 1571.31   133.3 1567.28
   142.8 1565.15     1661562.322   171.6 1561.77   179.5 1562.27   190.7 1563.16
   200.3 1563.08   209.9 1562.38   229.1 1561.96   248.2 1561.04   257.8 1561.13
   267.4 1561.51   286.6 1561.35   296.2 1562.35   315.4 1567.11   324.9 1568.47
   344.1 1570.48   353.7 1571.66   382.5 1575.91     392 1577.75   401.6 1581.42
#Mann= 3 , 0 , 0
       0     .08       0     166    .045       0   179.5     .08       0
#XS Ineff= 2 , 0
                          195.75          1567.7
Permanent Ineff=
       F       F
Bank Sta=166,179.5
XS Rating Curve= 0 ,0
Exp/Cntr=0.3,0.1

Type RM Length L Ch R = 1 ,17490.9 ,132.3,120.5,108.5
XS GIS Cut Line= 3
     1858126.403      361965.875     1858217.578      361971.083
     1858378.237      362135.789
#Sta/Elev= 29
       0 1577.67    27.4 1573.73    45.7 1571.24    54.8  1570.1    73.1 1568.02
    91.3 1565.82   100.9 1563.58   110.5 1559.92   120.1 1556.42   126.9 1554.92
   129.7  1554.3   139.3 1554.94   158.4 1557.66     168 1558.28   177.6 1558.42
   187.2 1558.24   196.8 1556.66   206.4 1553.25     216 1550.78   225.5  1550.4
   235.1 1550.75   244.7 1552.19   254.3 1555.29   263.9 1558.21   273.5 1560.52
   292.6 1565.47   302.2 1567.38   311.8 1568.56   321.4 1569.38
#Mann= 3 , 0 , 0
       0     .08       0   126.9    .045       0   139.3     .08       0
#XS Ineff= 2 , 0
                          178.26         1563.24
Permanent Ineff=
       F       F
Bank Sta=126.9,139.3
XS Rating Curve= 0 ,0
Exp/Cntr=0.3,0.1

Type RM Length L Ch R = 1 ,17370.3 ,43.4,62.2,84.8
XS GIS Cut Line= 3
      1858086.06      362068.526     1858163.295      362098.632
     1858369.138      362155.354
#Sta/Elev= 30
       0 1590.11     9.2 1582.76    18.4 1577.08    27.6  1573.6    36.8 1571.71
    64.5 1567.26    73.7 1565.11    82.9 1561.03    92.6 1555.74     101 1552.89
   102.3 1552.45     112 1552.43     116 1553.02   121.7 1553.85   131.4 1554.96
   141.1 1555.48   150.8 1555.75   170.2 1556.52     180 1556.34   189.6 1554.88
   199.4 1552.63   209.1 1553.12   218.8 1555.82   228.5 1556.81   238.2 1558.11
   247.9 1560.12   267.3 1565.39     277  1567.3   286.7 1568.46   296.4 1569.37
#Mann= 3 , 0 , 0
       0     .08       0     101    .045       0     116     .08       0
#XS Ineff= 2 , 0
                           167.4         1566.33
Permanent Ineff=
       F       F
Bank Sta=101,116
XS Rating Curve= 0 ,0
Exp/Cntr=0.3,0.1

Type RM Length L Ch R = 1 ,17308.1 ,77,80.1,190.8
XS GIS Cut Line= 6
     1858068.299       362083.28      1858128.35      362112.258
      1858192.75      362213.477     1858200.809      362239.403
     1858166.488      362342.345       1858283.8        362375.6
#Sta/Elev= 30
       0 1600.53      19 1584.34    28.6 1577.22    38.1 1572.81    47.6 1570.58
    75.9 1566.18    85.1 1564.03    94.4 1560.37   103.6  1555.8   112.8 1552.08
     122 1550.45     1441550.103   168.2 1551.26   186.6 1551.35   204.8 1550.24
   222.8 1547.67   249.8 1545.21   258.5 1545.12   275.8 1546.76   284.4 1547.19
   293.9 1547.08   322.5 1545.03   341.2 1545.18     360 1546.61   369.4 1547.76
   378.8 1549.39   388.1 1552.12   397.5 1556.01   416.3 1565.29   444.4 1581.25
#Mann= 3 , 0 , 0
       0     .08       0     122    .045       0     144     .08       0
#XS Ineff= 2 , 0
                          181.58         1564.91
Permanent Ineff=
       F       F
Bank Sta=122,144
XS Rating Curve= 0 ,0
Exp/Cntr=0.3,0.1

Type RM Length L Ch R = 1 ,17228   ,171.6,150.9,17.7
XS GIS Cut Line= 6
     1858023.928       362114.02     1858083.979      362142.998
     1858148.379      362244.217     1858156.438      362270.143
     1858124.374      362371.869     1858265.479      362400.955
#Sta/Elev= 30
       0 1625.06      19 1609.23    47.6  1582.4    57.2 1575.64    66.7 1570.96
    75.9 1568.29    85.1 1566.63   103.6 1564.68   131.3 1559.04   140.5  1557.9
   149.7 1556.05   168.2 1546.96   172.2 1545.95   177.4 1544.63   186.6 1544.73
   195.7 1545.69   213.8 1547.14   291.4 1542.08   310.8 1542.26   320.5 1541.88
   330.1 1542.67   358.9 1541.06   387.7 1540.69   397.3 1541.29   406.9 1543.33
   416.5 1546.64   426.1 1550.71   435.7 1555.39   445.3 1560.64   464.5  1572.5
#Mann= 3 , 0 , 0
       0     .08       0   172.2    .045       0   195.7     .08       0
#XS Ineff= 2 , 0
                          214.79         1557.73
Permanent Ineff=
       F       F
Bank Sta=172.2,195.7
XS Rating Curve= 0 ,0
Exp/Cntr=0.3,0.1

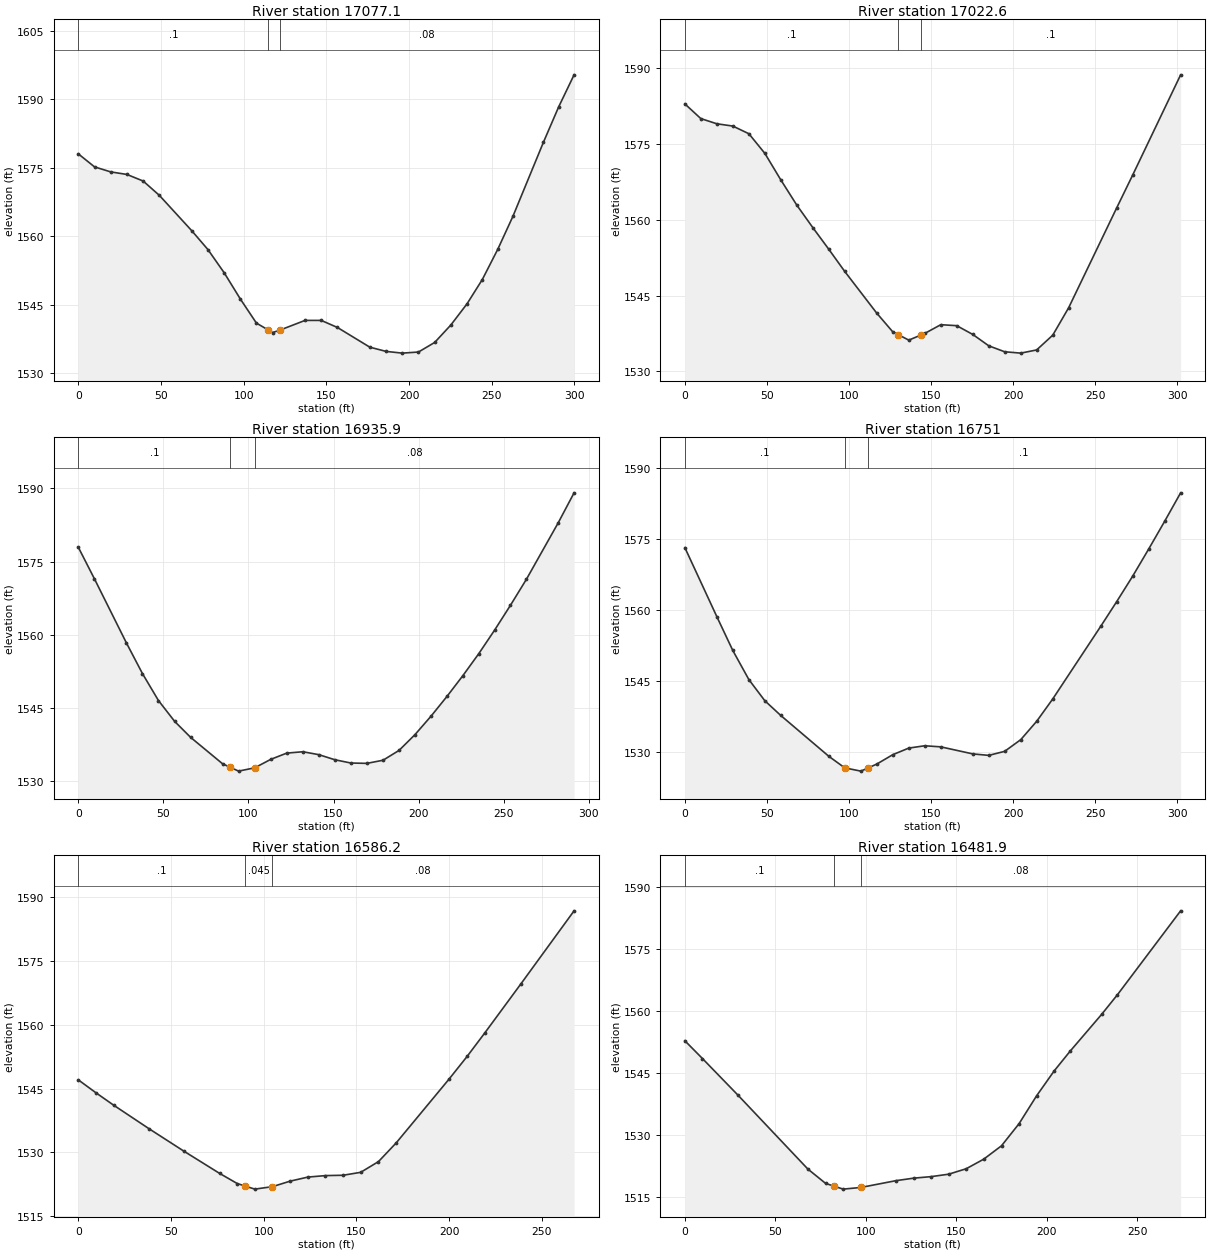
Type RM Length L Ch R = 1 ,17077.1 ,53.8,54.5,55.3
XS GIS Cut Line= 3
     1857991.783      362348.268     1858216.106      362418.545
     1858274.321      362446.767
#Sta/Elev= 30
       0 1578.05     9.8  1575.2    19.6  1574.1    29.4 1573.54    39.2  1572.1
      49 1568.96    68.6 1561.21    78.4 1557.07    88.2    1552      98 1546.24
   107.7 1540.97     1151539.428   117.5  1538.9     1221539.445   137.1 1541.56
   146.9 1541.56   156.7 1540.01   176.3 1535.69   186.1 1534.77   195.9 1534.39
   205.7 1534.63   215.5 1536.73   225.3 1540.56   235.1 1545.21   244.3 1550.51
   253.6  1557.1   262.8 1564.35   281.3 1580.62   290.5 1588.36   299.8 1595.37
#Mann= 3 , 0 , 0
       0      .1       0     115    .045       0     122     .08       0
Bank Sta=115,122
XS Rating Curve= 0 ,0
Exp/Cntr=0.3,0.1

Type RM Length L Ch R = 1 ,17022.6 ,84,86.7,89.3
XS GIS Cut Line= 2
      1857959.74      362390.377     1858244.649      362490.578
#Sta/Elev= 29
       0  1582.9     9.7    1580    19.5 1578.97    29.2 1578.52      39    1577
    48.7 1573.13    58.4  1567.9    68.2 1562.88    77.9 1558.46    87.7 1554.15
    97.4 1549.77   116.9 1541.53   126.6 1537.85     1301537.281   136.4  1536.2
     1441537.236   146.1 1537.52   155.9 1539.25   165.6 1539.06   175.4 1537.32
   185.1 1535.08   194.8  1533.9   204.6 1533.63   214.3 1534.26   224.1 1537.18
   233.8 1542.61     263 1562.31   272.8 1568.84     302 1588.65
#Mann= 3 , 0 , 0
       0      .1       0     130    .045       0     144      .1       0
Bank Sta=130,144
XS Rating Curve= 0 ,0
Exp/Cntr=0.3,0.1

Type RM Length L Ch R = 1 ,16935.9 ,186,184.9,183.6
XS GIS Cut Line= 3
     1857961.877      362470.549     1858148.254      362561.433
     1858228.559      362586.243
#Sta/Elev= 30
       0 1577.94     9.4 1571.53    28.3 1558.33    37.7 1552.07    47.1 1546.55
    56.6 1542.29      66 1539.01    84.8 1533.59    89.4 1532.86    94.2 1532.09
   103.7 1532.77   113.1  1534.5   122.5 1535.78     132 1536.06   141.4 1535.46
   150.8 1534.42   160.2 1533.75   169.6 1533.68   179.1 1534.32   188.5 1536.33
   197.9 1539.57   207.4 1543.38   216.7  1547.4     226 1551.63   235.4 1556.16
   244.7 1560.98     254 1566.06   263.4  1571.4   282.1 1582.97   291.4  1589.1
#Mann= 3 , 0 , 0
       0      .1       0    89.4    .045       0   103.7     .08       0
Bank Sta=89.4,103.7
XS Rating Curve= 0 ,0
Exp/Cntr=0.3,0.1

Type RM Length L Ch R = 1 ,16751   ,164.3,164.7,165
XS GIS Cut Line= 2
     1857870.255      362637.702      1858148.32       362755.57
#Sta/Elev= 27
       0 1573.19    19.5 1558.58    29.2 1551.45      39 1545.29    48.7 1540.83
    58.4 1537.72    87.7 1529.08    97.4 1526.64   107.2 1525.95   111.31526.578
   116.9 1527.44   126.6 1529.42   136.4 1530.82   146.1 1531.31   155.9 1531.08
   175.4 1529.59   185.1 1529.28   194.8 1530.13   204.6  1532.6   214.3 1536.48
   224.1 1541.21   253.3 1556.55     263 1561.75   272.8 1567.17   282.5 1572.87
   292.3 1578.78     302 1584.78
#Mann= 3 , 0 , 0
       0      .1       0    97.4    .045       0   111.3      .1       0
Bank Sta=97.4,111.3
XS Rating Curve= 0 ,0
Exp/Cntr=0.3,0.1

Type RM Length L Ch R = 1 ,16586.2 ,101.9,104.3,106.6
XS GIS Cut Line= 3
     1857823.243      362793.915     1857997.262      362871.231
     1858064.347      362909.054
#Sta/Elev= 22
       0 1547.04     9.5 1544.01      19 1541.11    38.1 1535.57    57.1 1530.24
    76.2 1525.06    85.7 1522.68    89.91522.093    95.2 1521.36   104.7 1521.94
   114.2 1523.23   123.8 1524.19   133.3 1524.54   142.8 1524.62   152.3 1525.31
   161.9 1527.83   171.4  1532.2     200 1547.24   209.7 1552.55   219.3 1558.11
   238.6 1569.54   267.4 1586.78
#Mann= 3 , 0 , 0
       0      .1       0    89.9    .045       0   104.7     .08       0
Bank Sta=89.9,104.7
XS Rating Curve= 0 ,0
Exp/Cntr=0.3,0.1

Type RM Length L Ch R = 1 ,16481.9 ,368.7,369.1,369.1
XS GIS Cut Line= 3
     1857778.618      362876.973     1857955.597      362978.673
      1858023.64       362994.71
#Sta/Elev= 22
       0 1552.82     9.7 1548.53    29.2 1539.74      68  1521.8    77.8 1518.34
    82.61517.655    87.5 1516.96    97.2 1517.36   116.6    1519   126.4 1519.61
   136.1 1519.98   145.8 1520.57   155.5 1521.89   165.2 1524.21     175 1527.44
   184.7 1532.78   194.4 1539.52   204.1 1545.53   212.9 1550.29   230.3 1559.18
   239.1 1563.96     274 1584.23
#Mann= 3 , 0 , 0
       0      .1       0    82.6    .045       0    97.2     .08       0
Bank Sta=82.6,97.2
XS Rating Curve= 0 ,0
Exp/Cntr=0.3,0.1

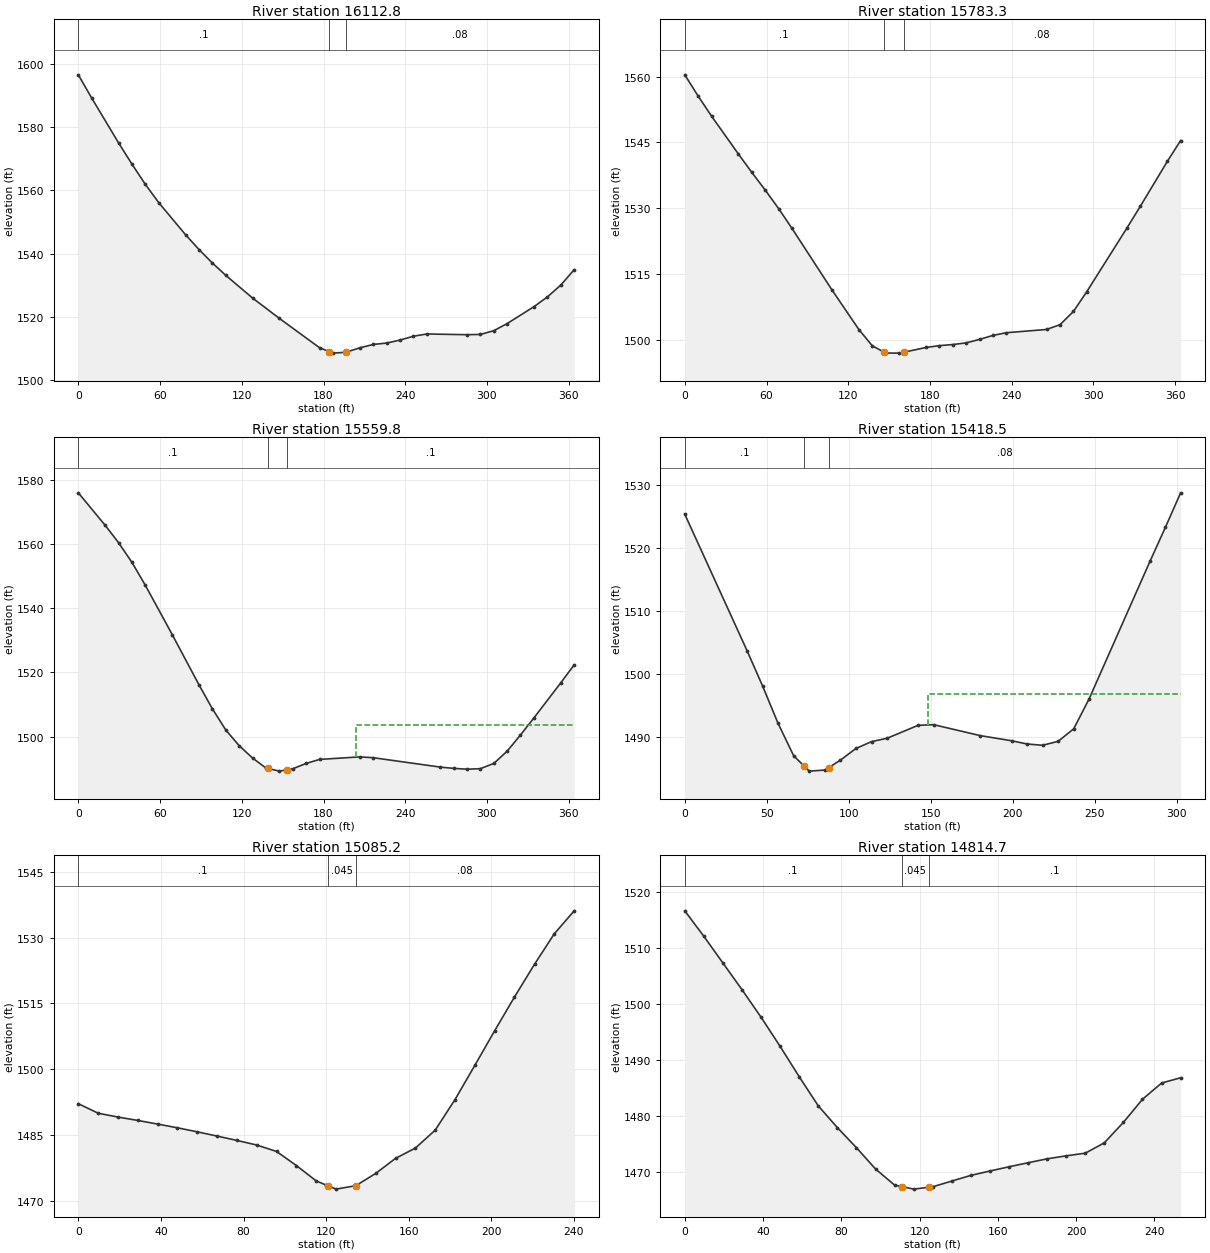
Type RM Length L Ch R = 1 ,16112.8 ,335.6,329.5,323.1
XS GIS Cut Line= 2
     1857535.834      363157.602     1857849.722      363341.993
#Sta/Elev= 30
       0 1596.52     9.8  1589.2    29.5 1575.04    39.4 1568.29    49.2 1561.92
      59 1556.16    78.7 1546.01    88.6 1541.32    98.4 1537.07   108.2 1533.19
   127.9 1526.01   147.6 1519.57   177.1  1510.3   184.3 1509.05   186.9  1508.6
   196.3 1508.87   206.6 1510.26   216.5 1511.34   226.3 1511.78   236.1 1512.72
     246 1513.94   255.8 1514.65   285.3 1514.42   295.2 1514.51     305 1515.69
   314.8 1517.93   334.5 1523.28   344.4 1526.37   354.2  1530.1     364 1534.96
#Mann= 3 , 0 , 0
       0      .1       0   184.3    .045       0   196.3     .08       0
Bank Sta=184.3,196.3
XS Rating Curve= 0 ,0
Exp/Cntr=0.3,0.1

Type RM Length L Ch R = 1 ,15783.3 ,225.1,223.5,221.6
XS GIS Cut Line= 2
     1857408.994      363510.384     1857761.337      363601.809
#Sta/Elev= 30
       0 1560.43     9.8 1555.58    19.7 1550.97    39.4 1542.34    49.2 1538.17
      59 1534.14    68.9  1529.9    78.7 1525.38   108.2 1511.27   127.9 1502.26
   137.7 1498.57   145.9 1497.22   147.6 1496.94   157.4 1496.92   160.9 1497.14
   177.1 1498.21   186.9 1498.63   196.8 1498.88   206.6 1499.26   216.4 1500.05
   226.3 1500.97   236.1 1501.58   265.6 1502.32   275.5 1503.42   285.3 1506.43
   295.1 1510.94   324.7 1525.53   334.5 1530.48   354.2 1540.66     364 1545.44
#Mann= 3 , 0 , 0
       0      .1       0   145.9    .045       0   160.9     .08       0
Bank Sta=145.9,160.9
XS Rating Curve= 0 ,0
Exp/Cntr=0.3,0.1

Type RM Length L Ch R = 1 ,15559.8 ,144,141.3,138.5
XS GIS Cut Line= 2
     1857371.612      363741.535     1857729.976      363805.341
#Sta/Elev= 30
       0 1575.88    19.7 1565.78    29.5 1560.39    39.4 1554.22    49.2 1547.11
    68.9 1531.81    88.5 1516.21    98.4 1508.71   108.2 1502.14     118 1497.26
   127.9 1493.39   137.7 1490.29   139.21490.141   147.6 1489.31   153.2 1489.73
   157.4 1490.04   167.2  1491.7   177.1 1492.95   206.6 1493.74   216.4 1493.49
   265.6 1490.57   275.5 1490.17   285.3 1489.91   295.1 1490.07     305 1491.69
   314.8 1495.52   324.6 1500.56   334.5 1505.88   354.2  1516.8     364 1522.36
#Mann= 3 , 0 , 0
       0      .1       0   139.2    .045       0   153.2      .1       0
#XS Ineff= 2 , 0
                          203.72          1503.6
Permanent Ineff=
       F       F
Bank Sta=139.2,153.2
XS Rating Curve= 0 ,0
Exp/Cntr=0.3,0.1

Type RM Length L Ch R = 1 ,15418.5 ,314.2,333.3,351.2
XS GIS Cut Line= 3
     1857414.446      363902.425     1857651.298      363915.463
     1857699.942       363958.91
#Sta/Elev= 25
       0 1525.41      38 1503.74    47.4 1498.18    56.9 1492.21    66.4 1487.08
    72.7 1485.46    75.9 1484.64    85.4 1484.81    87.7 1485.19    94.9 1486.38
   104.4 1488.24   113.9 1489.32   123.4 1489.86   142.3 1491.91   151.8 1492.01
   180.3 1490.27   199.3 1489.46   208.7 1488.95   218.2 1488.74   227.7 1489.37
   237.2 1491.36   246.5 1496.06   283.8 1517.99   293.1 1523.33   302.4 1528.81
#Mann= 3 , 0 , 0
       0      .1       0    72.7    .045       0    87.7     .08       0
#XS Ineff= 2 , 0
                          148.18          1496.9
Permanent Ineff=
       F       F
Bank Sta=72.7,87.7
XS Rating Curve= 0 ,0
Exp/Cntr=0.3,0.1

Type RM Length L Ch R = 1 ,15085.2 ,277.9,270.4,262.6
XS GIS Cut Line= 2
     1857345.892      364107.382      1857501.32      364290.333
#Sta/Elev= 29
       0 1492.12     9.6 1489.95    19.2 1489.07    28.8  1488.3    38.4 1487.47
      48 1486.62    57.6  1485.7    67.2 1484.73    76.8 1483.74    86.4 1482.69
      96 1481.22   105.6 1478.01   115.2  1474.5   119.7 1473.62   120.71473.426
   124.8 1472.63   134.4 1473.42   134.7 1473.51     144 1476.21   153.6 1479.65
   163.2 1481.99   172.8 1486.08   182.4 1493.06     192 1500.86   201.6 1508.76
   211.2 1516.46   220.9 1523.93   230.5 1530.89   240.1 1536.12
#Mann= 3 , 0 , 0
       0      .1       0   120.7    .045       0   134.4     .08       0
Bank Sta=120.7,134.4
XS Rating Curve= 0 ,0
Exp/Cntr=0.3,0.1

Type RM Length L Ch R = 1 ,14814.7 ,225.3,214.8,204.1
XS GIS Cut Line= 2
     1857121.019      364316.536     1857339.838      364444.354
#Sta/Elev= 30
       0 1516.68     9.8 1512.09    19.5 1507.33    29.2 1502.58      39 1497.62
    48.7 1492.42    58.5 1486.96    68.2 1481.77      78 1477.85    87.7 1474.28
    97.5 1470.45   107.2 1467.58   109.8 1467.39   110.81467.315     117 1466.85
   124.8 1467.19   126.7 1467.27   136.4 1468.29   146.2 1469.31     156  1470.1
   165.7 1470.85   175.4 1471.57   185.2 1472.28   194.9 1472.81   204.7 1473.29
   214.4 1475.14   224.2 1478.82   233.9 1482.94   243.7 1485.85   253.4 1486.79
#Mann= 3 , 0 , 0
       0      .1       0   110.8    .045       0   124.8      .1       0
Bank Sta=110.8,124.8
XS Rating Curve= 0 ,0
Exp/Cntr=0.3,0.1

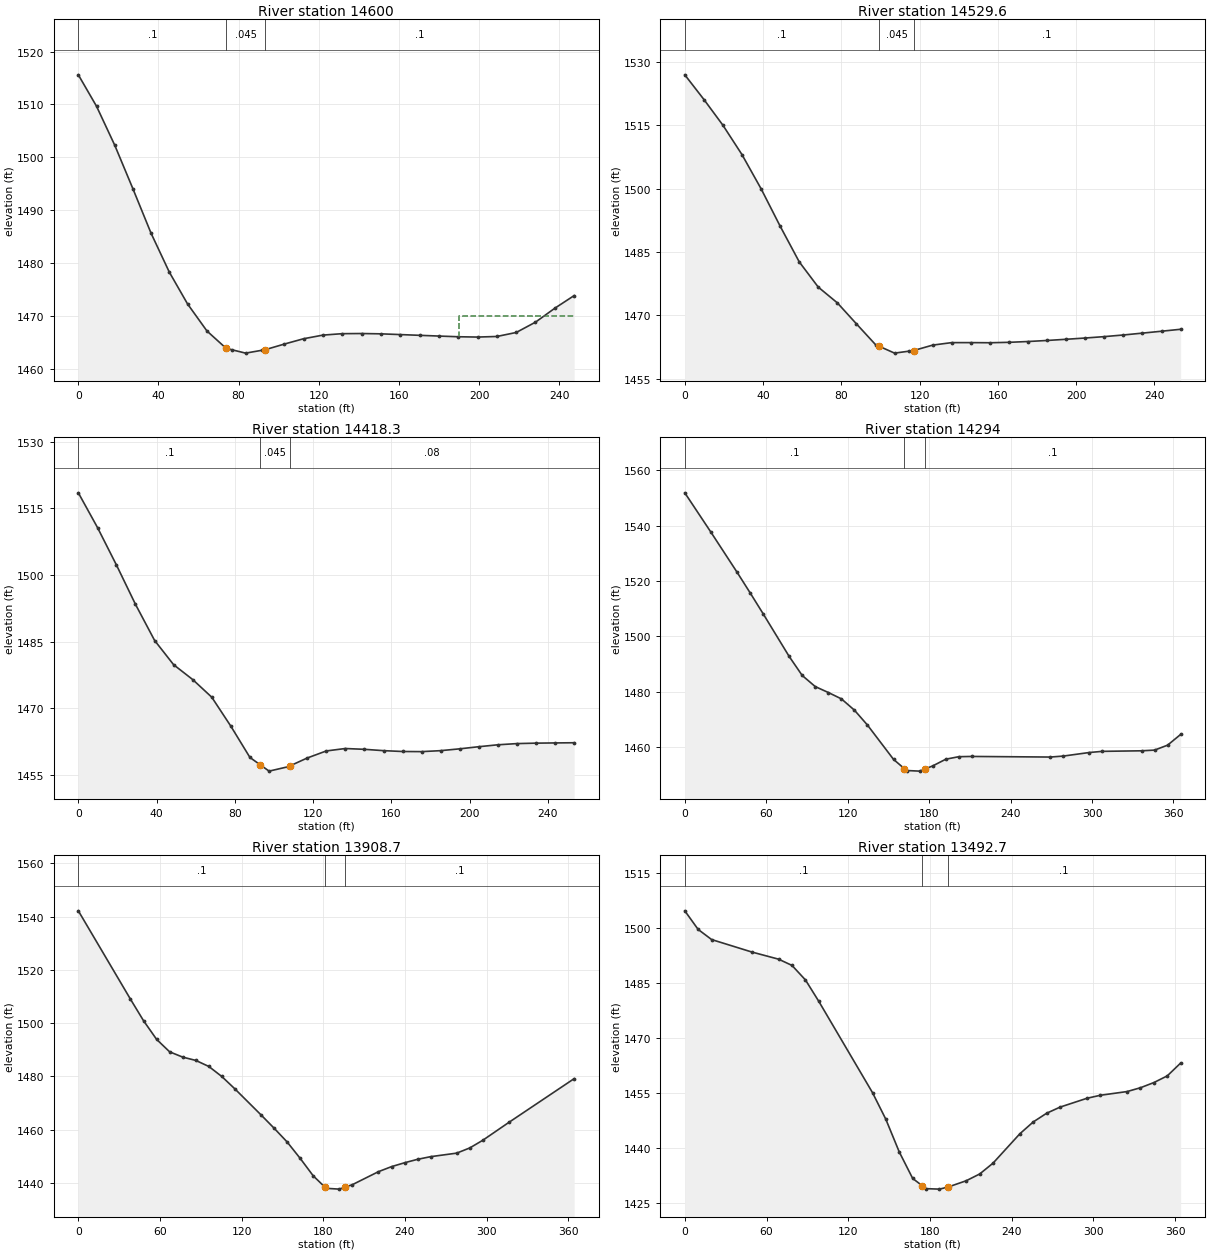
Type RM Length L Ch R = 1 ,14600   ,60.1,70.4,80.2
XS GIS Cut Line= 3
     1857114.281      364570.433     1857167.046      364584.116
     1857359.684       364595.86
#Sta/Elev= 29
       0 1515.59     9.1 1509.63    18.2 1502.25    27.3 1493.98    36.3 1485.62
    45.4 1478.27    54.5 1472.25    64.2 1467.12    73.8 1463.83    76.5 1463.58
    83.5 1462.93    91.5 1463.46    93.1 1463.56   102.8 1464.64   112.4 1465.65
   122.1 1466.34   131.7 1466.61   141.4 1466.64     151 1466.58   160.7 1466.44
   170.3  1466.3     180 1466.16   189.6 1466.03   199.3 1465.97   208.9 1466.08
   218.6 1466.84   228.2 1468.79   237.9 1471.44   247.5 1473.82
#Mann= 3 , 0 , 0
       0      .1       0    73.8    .045       0    93.1      .1       0
#XS Ineff= 2 , 0
       0                     190       0    1470
Permanent Ineff=
       F       F
Bank Sta=73.8,93.1
XS Rating Curve= 0 ,0
Exp/Cntr=0.3,0.1

Type RM Length L Ch R = 1 ,14529.6 ,111.4,111.3,111.2
XS GIS Cut Line= 2
     1857081.364      364599.737      1857303.09      364722.444
#Sta/Elev= 29
       0 1526.93     9.8 1521.07    19.5 1514.98    29.2 1508.05      39 1499.93
    48.7 1491.11    58.5 1482.62    68.2 1476.65      78  1472.9    87.7 1467.95
    97.5 1463.01    99.5  1462.6   107.2 1461.01   114.5 1461.47     117 1461.63
   126.7 1462.91   136.4  1463.5   146.2  1463.5     156 1463.47   165.7 1463.57
   175.4 1463.76   185.2 1464.01   194.9 1464.29   204.7 1464.59   214.4 1464.92
   224.2 1465.31   233.9 1465.75   243.7  1466.2   253.4 1466.66
#Mann= 3 , 0 , 0
       0      .1       0    99.5    .045       0     117      .1       0
Bank Sta=99.5,117
XS Rating Curve= 0 ,0
Exp/Cntr=0.3,0.1

Type RM Length L Ch R = 1 ,14418.3 ,119.5,124.3,128.6
XS GIS Cut Line= 2
     1857026.894      364696.819     1857249.195       364818.48
#Sta/Elev= 29
       0 1518.48     9.8 1510.66    19.5 1502.21    29.2 1493.38      39 1485.23
    48.7 1479.78    58.5 1476.42    68.2 1472.46      78  1465.9    87.7  1458.9
      93 1457.23    97.5 1455.82   107.2 1456.81     108 1456.97     117 1458.78
   126.7 1460.36   136.4 1460.91   146.2 1460.73     156 1460.43   165.7 1460.24
   175.4 1460.21   185.2 1460.43   194.9 1460.84   204.7 1461.32   214.4 1461.75
   224.2 1462.02   233.9 1462.12   243.7 1462.17   253.4 1462.21
#Mann= 3 , 0 , 0
       0      .1       0      93    .045       0     108     .08       0
Bank Sta=93,108
XS Rating Curve= 0 ,0
Exp/Cntr=0.3,0.1

Type RM Length L Ch R = 1 ,14294   ,383.5,385.3,385.9
XS GIS Cut Line= 2
     1856927.325      364744.794     1857206.056      364980.953
#Sta/Elev= 29
       0 1551.87    19.2 1537.68    38.5 1523.17    48.1 1515.74    57.7 1508.16
    76.9 1492.71    86.5 1485.84    96.1 1481.82   105.8 1479.66   115.4 1477.37
     125 1473.28   134.6 1467.89   153.8 1455.49   161.7 1452.18   163.4 1451.47
     173 1451.25     1771452.029   182.7 1453.15   192.3 1455.56   201.9 1456.47
   211.5 1456.56   269.2 1456.34   278.8 1456.69     298 1457.98   307.6  1458.4
   336.5  1458.6   346.1 1458.85   355.7 1460.64   365.3 1464.51
#Mann= 3 , 0 , 0
       0      .1       0   161.7    .045       0     177      .1       0
Bank Sta=161.7,177
XS Rating Curve= 0 ,0
Exp/Cntr=0.3,0.1

Type RM Length L Ch R = 1 ,13908.7 ,428.7,416,402.2
XS GIS Cut Line= 2
      1856712.91      365034.627     1856980.107       365282.22
#Sta/Elev= 30
       0 1542.14    38.3 1508.98    47.9  1500.9    57.5  1493.9    67.1 1489.21
    76.7 1487.23    86.3 1485.99    95.9 1483.72   105.4 1479.96     115 1475.32
   134.2 1465.56   143.8 1460.57   153.4 1455.39     163 1449.23   172.6 1442.66
     181 1438.52   182.1 1437.98   191.7 1437.68     196 1438.42   201.3 1439.34
   220.5 1444.23   230.1 1446.12   239.7 1447.58   249.2 1448.86   258.8 1449.86
     278 1451.19   287.6 1453.14   297.2 1456.03   316.3 1462.72   364.3 1479.15
#Mann= 3 , 0 , 0
       0      .1       0     181    .045       0     196      .1       0
Bank Sta=181,196
XS Rating Curve= 0 ,0
Exp/Cntr=0.3,0.1

Type RM Length L Ch R = 1 ,13492.7 ,395.5,391.5,386.7
XS GIS Cut Line= 2
     1856452.149      365478.509     1856811.476      365536.939
#Sta/Elev= 30
       0 1504.68     9.8  1499.6    19.7 1496.83    49.2 1493.43    68.9 1491.47
    78.7 1489.77    88.6 1485.79    98.4 1479.94   137.8 1455.02   147.6 1447.74
   157.4 1438.86   167.3 1431.59   174.4 1429.57   177.1  1428.8   186.9 1428.67
     1931429.206   206.6 1430.96   216.5 1432.81   226.3 1435.77     246  1443.8
   255.8 1447.02   265.7 1449.41   275.5 1451.07   295.2 1453.48     305  1454.3
   324.7 1455.32   334.5 1456.36   344.4 1457.78   354.2  1459.6     364  1463.1
#Mann= 3 , 0 , 0
       0      .1       0   174.4    .045       0     193      .1       0
Bank Sta=174.4,193
XS Rating Curve= 0 ,0
Exp/Cntr=0.3,0.1

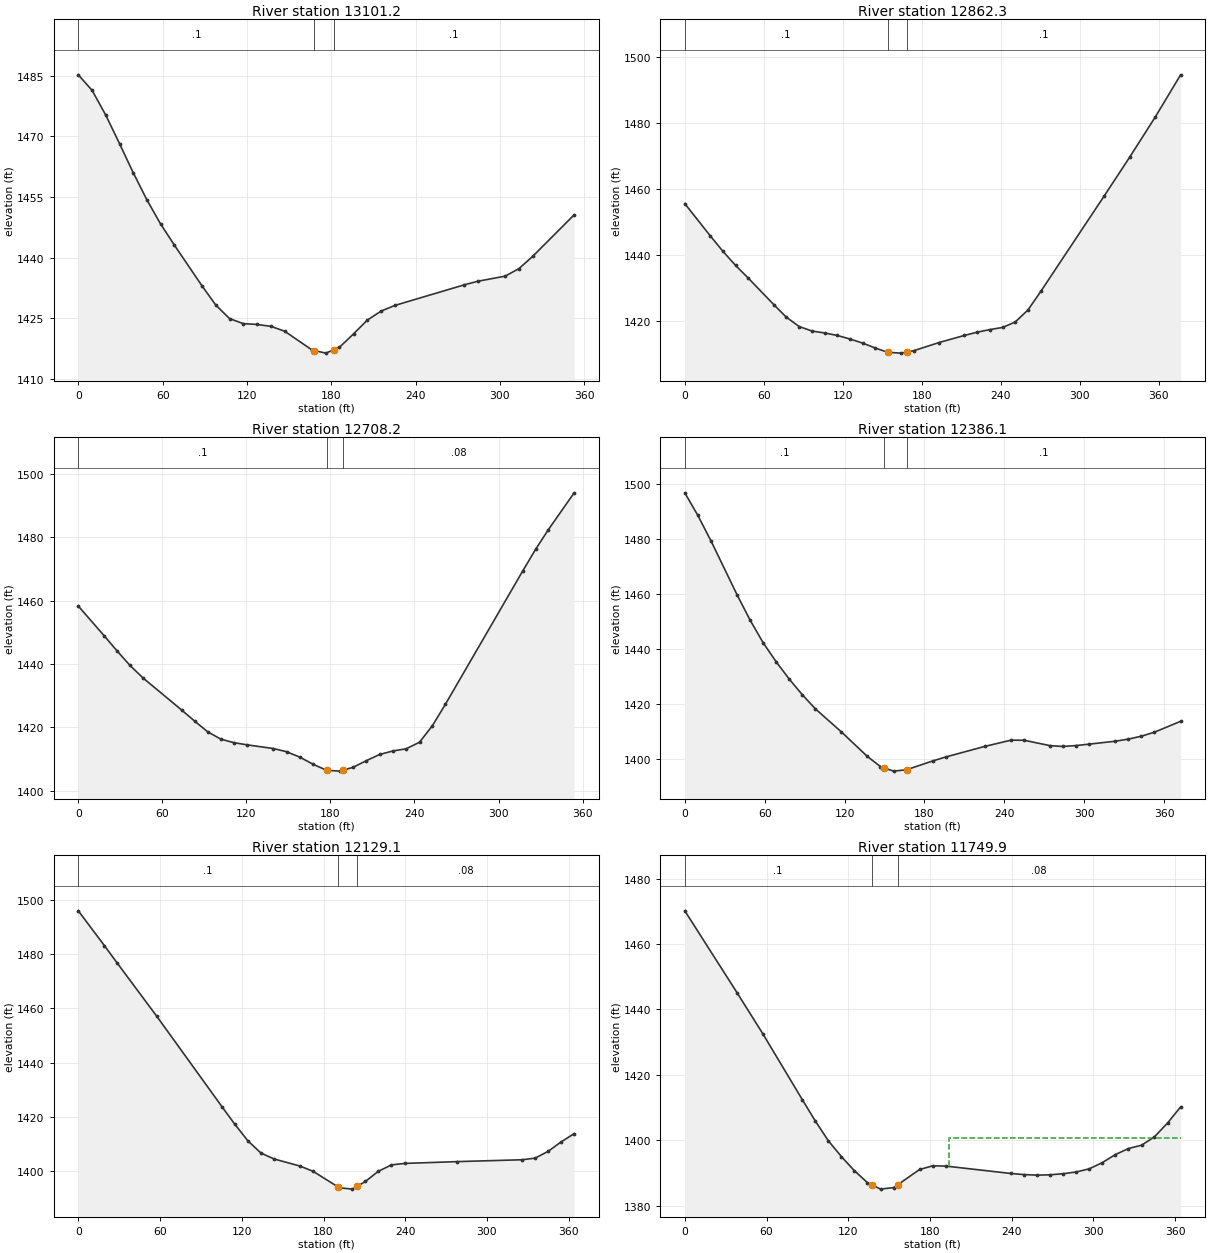
Type RM Length L Ch R = 1 ,13101.2 ,224.6,238.9,252.2
XS GIS Cut Line= 3
     1856463.923      365848.974     1856513.339       365880.36
     1856807.195      365865.735
#Sta/Elev= 30
       0 1485.23     9.8 1481.39    19.5 1475.28    29.3 1468.23      39 1461.07
    48.8 1454.32    58.5 1448.38    68.4  1443.1      88 1433.06    97.8 1428.31
   107.6 1424.97   117.4 1423.72   127.2 1423.52     137 1423.05   146.8 1421.85
   166.4 1417.18     1681417.056   176.2 1416.43     182  1417.3   185.8 1417.87
   195.8 1421.18   205.6 1424.59   215.5 1426.84   225.3 1428.23   274.3 1433.28
   284.1 1434.19   303.7 1435.46   313.5 1437.32   323.3 1440.35   352.8 1450.62
#Mann= 3 , 0 , 0
       0      .1       0     168    .045       0     182      .1       0
Bank Sta=168,182
XS Rating Curve= 0 ,0
Exp/Cntr=0.3,0.1

Type RM Length L Ch R = 1 ,12862.3 ,133.1,154.1,174.4
XS GIS Cut Line= 2
     1856420.378      366011.868     1856739.117      366212.395
#Sta/Elev= 30
       0 1455.52    19.3 1445.78      29 1441.04    38.6 1436.78    48.3  1432.9
    67.6  1424.9    77.2 1421.07    86.9 1418.25    96.6 1416.89   106.2 1416.31
   115.9 1415.54   125.5 1414.47   135.2 1413.22   144.8 1411.72   154.1 1410.44
   164.2 1410.19   169.1 1410.56   173.8 1410.91   193.1  1413.4   212.4 1415.56
   222.1 1416.54   231.7 1417.33   241.4 1417.98     251 1419.63   260.7  1423.3
   270.4 1428.91   318.6 1457.88     338 1469.67   357.3 1481.77   376.6 1494.58
#Mann= 3 , 0 , 0
       0      .1       0   154.1    .045       0   169.1      .1       0
Bank Sta=154.1,169.1
XS Rating Curve= 0 ,0
Exp/Cntr=0.3,0.1

Type RM Length L Ch R = 1 ,12708.2 ,332.1,322.2,311
XS GIS Cut Line= 4
     1856385.777      366043.481     1856446.056      366136.446
     1856460.462      366268.471     1856516.032      366363.892
#Sta/Elev= 30
       0 1458.24    18.5 1448.87    27.7  1444.1    36.9 1439.54    46.2  1435.6
    73.9 1425.45    83.1 1421.99    92.3 1418.66   101.6 1416.35   110.8 1415.24
   120.3 1414.54   139.3 1413.36   148.7 1412.36   158.2 1410.65   167.7 1408.39
   177.2 1406.53   186.7 1406.25     1891406.541   196.2 1407.46   205.7 1409.56
   215.2 1411.51   224.6  1412.6   234.1 1413.29   243.6 1415.36   252.8 1420.57
     262 1427.25   317.2 1469.25   326.4 1476.07   335.6 1482.33     354 1493.92
#Mann= 3 , 0 , 0
       0      .1       0   177.2    .045       0     189     .08       0
Bank Sta=177.2,189
XS Rating Curve= 0 ,0
Exp/Cntr=0.3,0.1

Type RM Length L Ch R = 1 ,12386.1 ,265.4,256.9,247.9
XS GIS Cut Line= 2
     1856068.433      366098.332     1856264.683      366414.892
#Sta/Elev= 30
       0  1496.9     9.8  1488.7    19.6  1479.5    39.2  1459.9      49 1450.68
    58.8 1442.46    68.6 1435.52    78.4 1429.24    88.2 1423.56      98 1418.43
   117.6 1410.01   137.2 1401.06     147 1397.39   149.5 1396.97   156.8 1395.74
   166.6 1396.24   186.2 1399.43     196 1400.88   225.4 1404.73     245 1406.99
   254.8 1406.97   274.4    1405   284.2  1404.7     294 1405.04   303.8 1405.55
   323.4 1406.61   333.2 1407.37     343 1408.44   352.8 1409.89   372.5 1413.85
#Mann= 3 , 0 , 0
       0      .1       0   149.5    .045       0   166.6      .1       0
Bank Sta=149.5,166.6
XS Rating Curve= 0 ,0
Exp/Cntr=0.3,0.1

Type RM Length L Ch R = 1 ,12129.1 ,379.1,379.2,379.1
XS GIS Cut Line= 3
     1855856.277       366328.03     1856003.469      366435.075
     1856150.661      366542.119
#Sta/Elev= 25
       0 1495.92    19.2 1483.07    28.7 1476.59    57.5 1457.16   105.4 1423.86
     115 1417.28   124.5 1411.25   134.1 1406.75   143.7 1404.58   162.8 1401.96
   172.4 1400.02   190.51394.336   191.6 1393.99   201.2 1393.48   204.51394.453
   210.7 1396.29   220.3 1400.07   229.9  1402.4   239.5 1402.94   277.8  1403.6
   325.7 1404.29   335.3 1404.88   344.8 1407.36   354.4 1410.85     364  1413.9
#Mann= 3 , 0 , 0
       0      .1       0   190.5    .045       0   204.5     .08       0
Bank Sta=190.5,204.5
XS Rating Curve= 0 ,0
Exp/Cntr=0.3,0.1

Type RM Length L Ch R = 1 ,11749.9 ,266,262.1,257.8
XS GIS Cut Line= 3
     1855668.723      366659.735     1855815.915       366766.78
     1855963.107      366873.824
#Sta/Elev= 30
       0 1470.16    38.3 1445.16    57.5 1432.41    86.2 1412.45    95.8 1405.89
   105.4 1399.81     115 1394.98   124.5 1390.67   134.1 1387.02   137.21386.382
   143.7 1385.04   153.3 1385.52   156.21386.348   172.4 1391.05     182 1392.17
   191.6 1392.09   239.5 1389.82     249 1389.49   258.6 1389.32   268.2 1389.42
   277.8 1389.76   287.4 1390.29     297 1391.26   306.5 1393.15   316.1 1395.61
   325.7 1397.46   335.3 1398.46   344.8 1401.05   354.4 1405.26     364 1410.19
#Mann= 3 , 0 , 0
       0      .1       0   137.2    .045       0   156.2     .08       0
#XS Ineff= 2 , 0
                           193.8         1400.66
Permanent Ineff=
       F       F
Bank Sta=137.2,156.2
XS Rating Curve= 0 ,0
Exp/Cntr=0.3,0.1

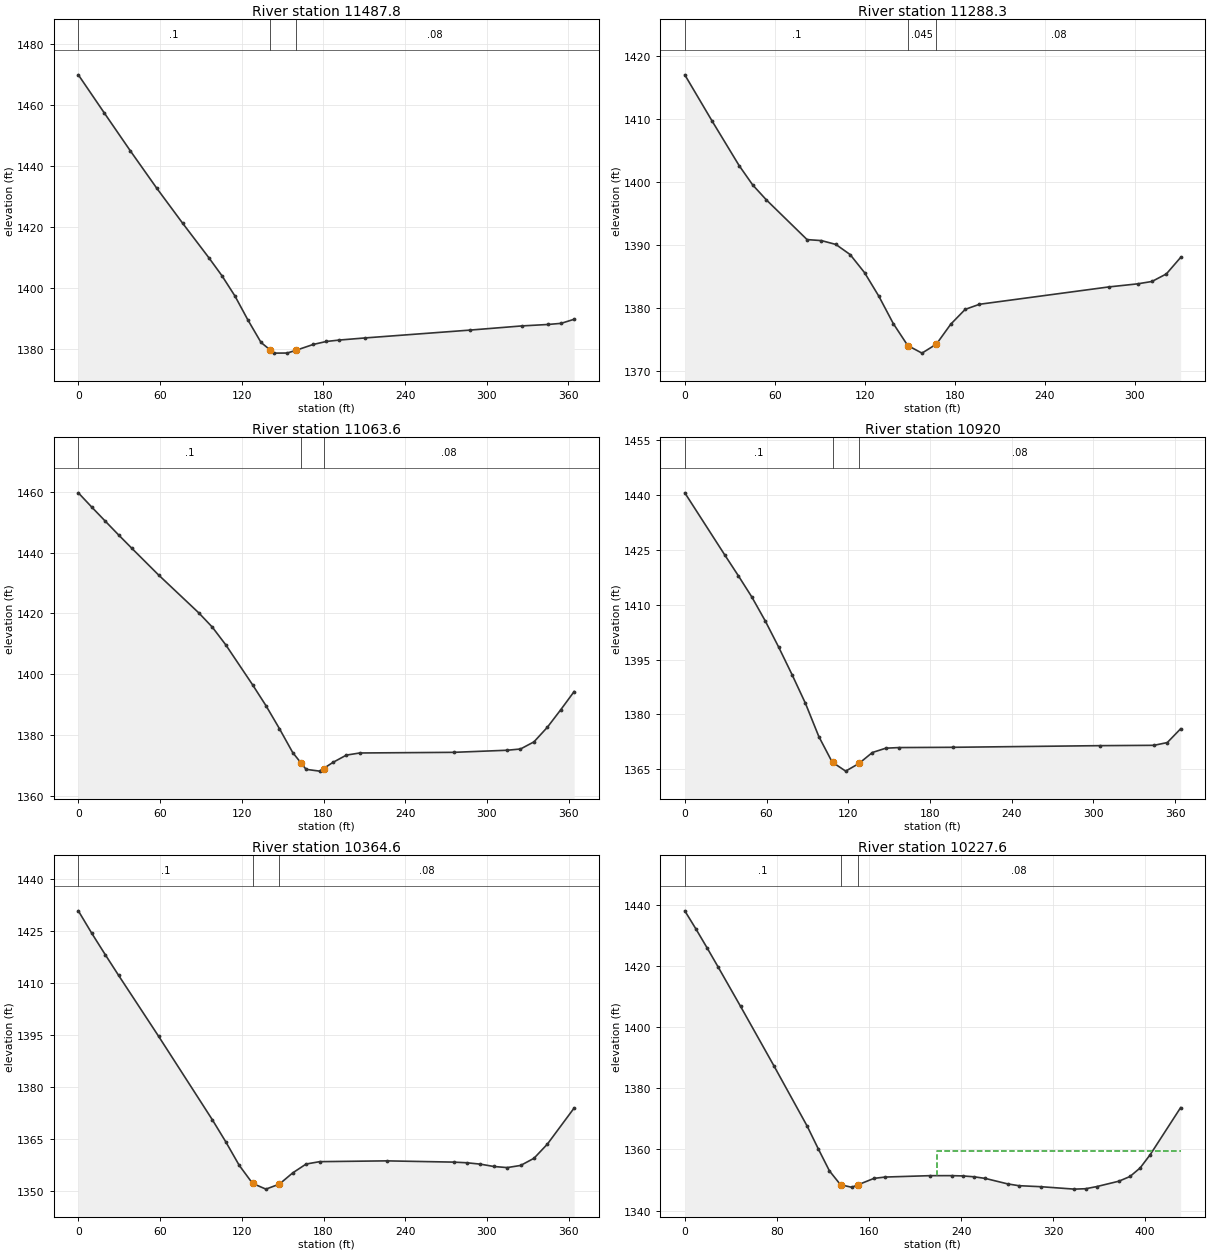
Type RM Length L Ch R = 1 ,11487.8 ,210.1,199.5,188.2
XS GIS Cut Line= 2
     1855504.425      366896.279     1855832.608      367054.184
#Sta/Elev= 23
       0 1469.93    19.2 1457.34    38.3 1444.93    57.5  1432.8    76.7  1421.2
    95.8 1409.97   105.4 1404.08     115  1397.4   124.6 1389.47   134.2 1382.13
   140.8 1379.72   143.8 1378.63   153.4 1378.66   159.81379.542   172.5 1381.47
   182.1 1382.45   191.7 1382.92   210.8 1383.62   287.5 1386.18   325.9 1387.56
     345 1388.03   354.6  1388.4   364.2 1389.74
#Mann= 3 , 0 , 0
       0      .1       0   140.8    .045       0   159.8     .08       0
Bank Sta=140.8,159.8
XS Rating Curve= 0 ,0
Exp/Cntr=0.3,0.1

Type RM Length L Ch R = 1 ,11288.3 ,212.2,224.7,237.4
XS GIS Cut Line= 3
     1855507.044      367077.677     1855538.266       367152.98
     1855787.117      367144.255
#Sta/Elev= 23
       0 1417.06    18.1 1409.75    36.2 1402.63    45.3 1399.53    54.4 1397.16
    81.5 1390.85    91.1 1390.69   100.7 1390.08   110.2 1388.47   119.8  1385.6
   129.4 1381.82     139 1377.48   148.6    1374   158.1 1372.79   167.7 1374.22
   177.3  1377.4   186.9 1379.75   196.4 1380.56   282.6 1383.32   301.8 1383.81
   311.4 1384.19     321 1385.39   330.5 1388.01
#Mann= 3 , 0 , 0
       0      .1       0   148.6    .045       0   167.7     .08       0
Bank Sta=148.6,167.7
XS Rating Curve= 0 ,0
Exp/Cntr=0.3,0.1

Type RM Length L Ch R = 1 ,11063.6 ,135.5,143.7,151.8
XS GIS Cut Line= 2
     1855384.879      367269.598     1855700.124      367451.579
#Sta/Elev= 27
       0 1459.66     9.8 1454.99    19.7 1450.38    29.5 1445.84    39.4 1441.36
      59  1432.6    88.5 1420.14    98.4 1415.46   108.2 1409.68   127.9 1396.53
   137.7 1389.68   147.6 1382.11   157.4 1374.21   163.4 1370.84   167.2  1368.7
   177.1 1368.11     1801368.959   186.9 1370.98   196.8 1373.38   206.6 1374.08
   275.5 1374.29   314.8 1374.98   324.6 1375.39   334.5 1377.74   344.3 1382.53
   354.2 1388.33     364  1394.3
#Mann= 3 , 0 , 0
       0      .1       0   163.4    .045       0     180     .08       0
Bank Sta=163.4,180
XS Rating Curve= 0 ,0
Exp/Cntr=0.3,0.1

Type RM Length L Ch R = 1 ,10920   ,576.8,555.4,533.8
XS GIS Cut Line= 2
     1855364.448      367372.352     1855595.001      367654.078
#Sta/Elev= 21
       0 1440.47    29.5 1423.43    39.4  1417.8    49.2 1412.06      59 1405.57
    68.9 1398.39    78.7  1390.9    88.6 1383.02    98.4 1373.98   108.2 1367.02
   108.5 1366.95   118.1 1364.55   127.9 1366.65   137.7 1369.63   147.6 1370.81
   157.4 1370.98   196.8 1371.05     305  1371.5   344.4 1371.59   354.2 1372.34
     364  1376.1
#Mann= 3 , 0 , 0
       0      .1       0   108.5    .045       0   127.9     .08       0
Bank Sta=108.5,127.9
XS Rating Curve= 0 ,0
Exp/Cntr=0.3,0.1

Type RM Length L Ch R = 1 ,10364.6 ,126.9,137,146.6
XS GIS Cut Line= 2
     1855035.811      367939.125     1855399.059      367915.415
#Sta/Elev= 24
       0 1430.92     9.8 1424.49    19.7 1418.32    29.5 1412.35      59  1394.7
    98.4 1370.66   108.2 1364.34   118.1 1357.54   127.9 1352.33   137.7 1350.67
   147.6 1352.12   157.4 1355.36   167.2  1357.9   177.1 1358.59   226.3 1358.82
   275.5 1358.46   285.3 1358.27   295.2 1357.87     305  1357.2   314.8 1356.88
   324.7  1357.5   334.5 1359.56   344.3 1363.63     364 1374.07
#Mann= 3 , 0 , 0
       0      .1       0   127.9    .045       0   147.6     .08       0
Bank Sta=127.9,147.6
XS Rating Curve= 0 ,0
Exp/Cntr=0.3,0.1

Type RM Length L Ch R = 1 ,10227.6 ,118.6,122.1,125.4
XS GIS Cut Line= 3
     1855013.082      368013.229     1855373.794      368153.003
     1855417.765      368152.077
#Sta/Elev= 30
       0 1438.04     9.7 1432.09    19.3 1425.97      29 1419.65    48.4 1406.83
    77.4 1387.38   106.4 1367.58     116 1360.19   125.7 1352.98   135.3 1348.47
   145.1 1347.63   150.3 1348.42   164.4 1350.55   174.1 1350.98   212.8 1351.43
   232.1 1351.44   241.8 1351.34   251.4 1351.06   261.1 1350.53   280.5 1348.74
   290.1 1348.16   309.5 1347.82   338.5 1347.03   348.2 1347.16   357.8 1347.85
   377.2 1349.63   386.8 1351.16   395.6 1353.95   404.4 1358.32   430.8 1373.69
#Mann= 3 , 0 , 0
       0      .1       0   135.3    .045       0   150.3     .08       0
#XS Ineff= 2 , 0
                          218.78         1359.64
Permanent Ineff=
       F       F
Bank Sta=135.3,150.3
XS Rating Curve= 0 ,0
Exp/Cntr=0.3,0.1