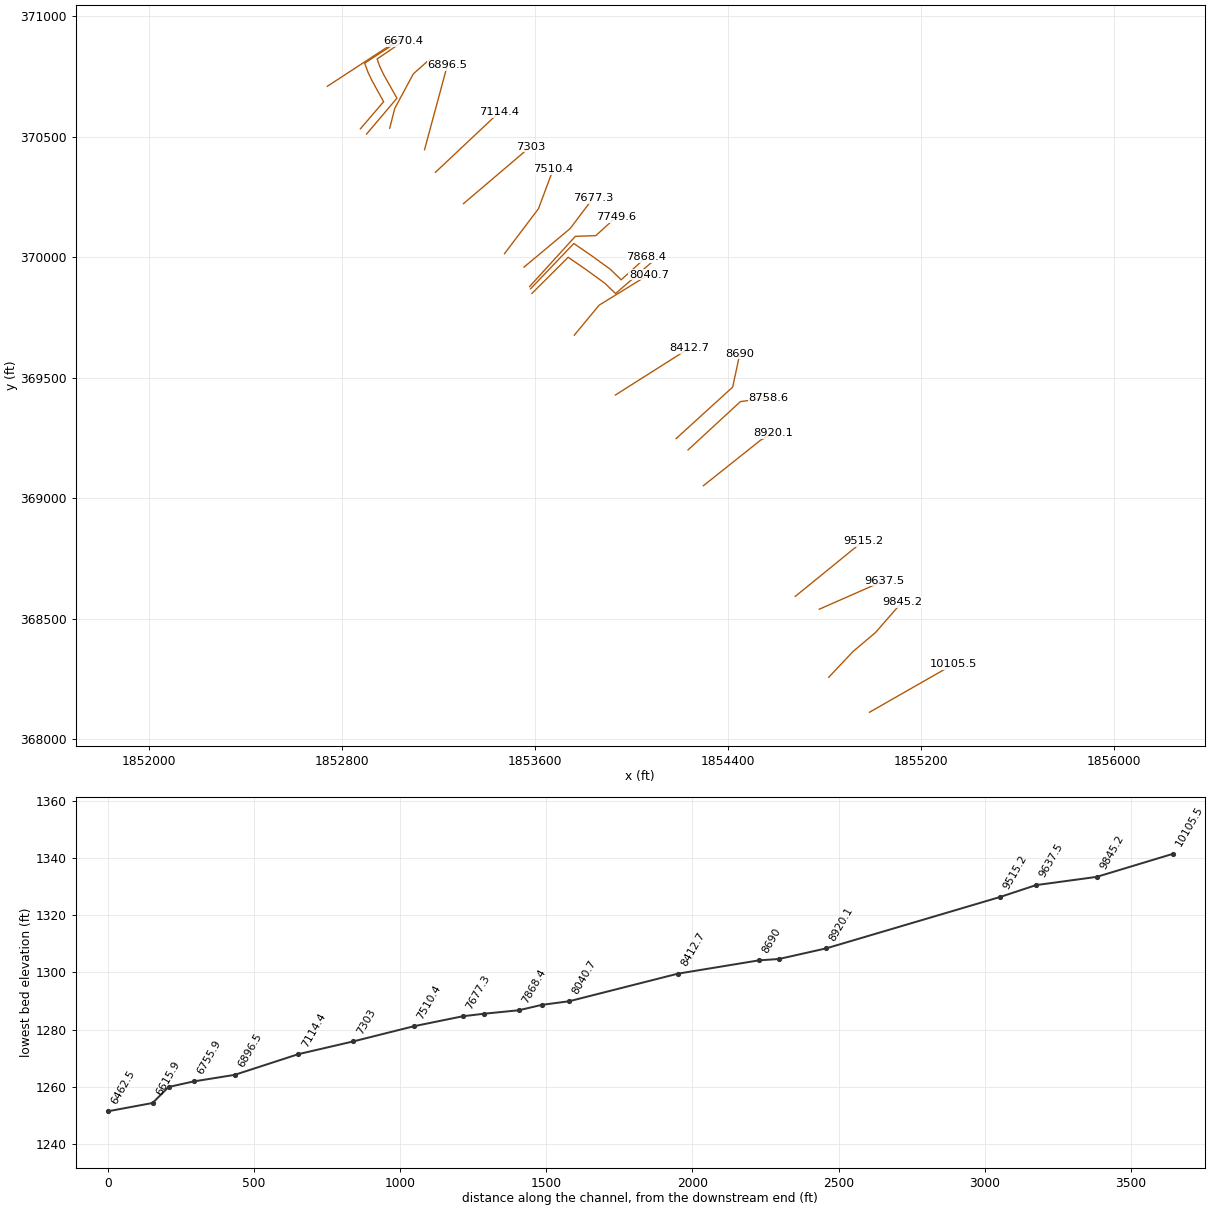
HEC-RAS study CABINCK.prj: CABINCK

--- CABINCK.g01 (geometry) --- (continued)

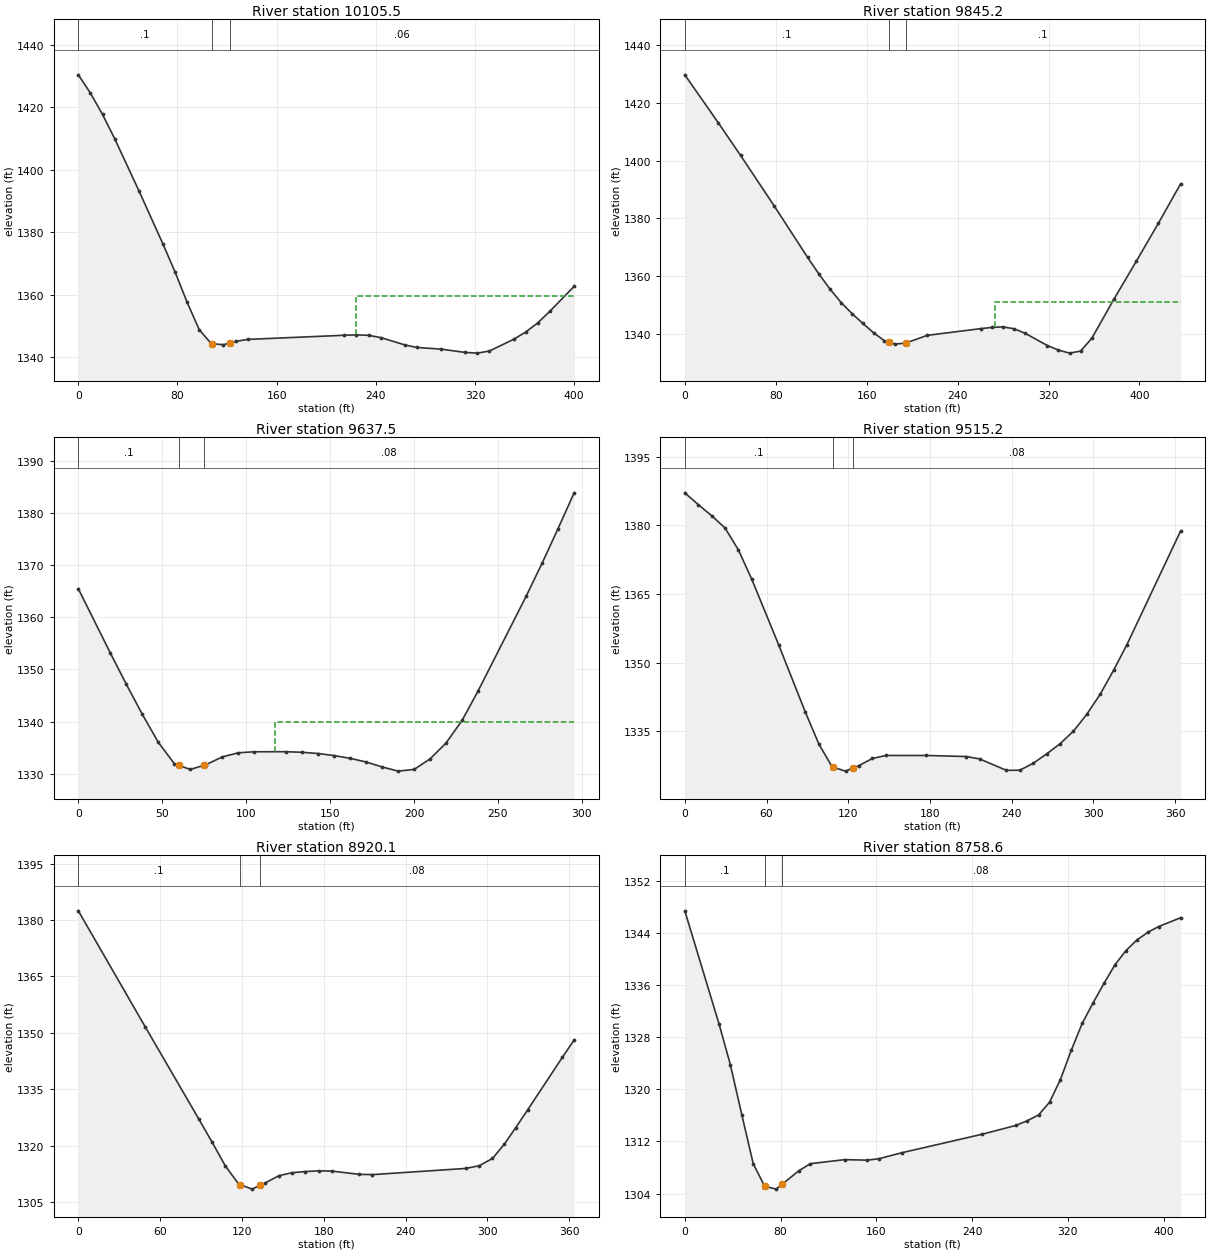
Type RM Length L Ch R = 1 ,10105.5 ,256.3,260.3,264.6
XS GIS Cut Line= 2
     1854984.563      368112.529     1855331.803      368310.983
#Sta/Elev= 30
       0 1430.44     9.8 1424.57    19.5 1417.77    29.3 1410.02    48.8 1393.41
    68.3 1376.28      78 1367.39    87.8 1357.61    97.6 1348.84   107.3 1344.41
   107.5  1344.4   117.1 1344.08   122.5 1344.66   126.8 1345.12   136.6 1345.77
   214.6  1347.1   224.4 1347.22   234.1 1347.08   243.9 1346.36   263.4 1344.01
   273.1 1343.19   292.6 1342.66   312.2  1341.6   321.9 1341.38   331.7 1342.07
   351.2 1345.81   360.9 1348.12   370.7 1351.08   380.4 1354.77     400 1362.76
#Mann= 3 , 0 , 0
       0      .1       0   107.5    .045       0   122.5     .06       0
#XS Ineff= 2 , 0
       0                   224.4       0 1359.77
Permanent Ineff=
       F       F
Bank Sta=107.5,122.5
XS Rating Curve= 0 ,0
Exp/Cntr=0.3,0.1

Type RM Length L Ch R = 1 ,9845.2  ,214,207.7,201
XS GIS Cut Line= 4
     1854815.691      368257.529     1854916.766      368364.679
     1855010.472      368443.987     1855119.612      368569.254
#Sta/Elev= 30
       0 1429.71    29.5 1413.09    49.1 1401.79    78.6 1384.35     108 1366.53
   117.8 1360.86   127.7 1355.56   137.5 1350.87   147.3 1346.98   156.7 1343.62
   166.2 1340.36   175.6 1337.64   179.4 1337.17   185.1 1336.47   194.4 1336.85
   213.4 1339.51   260.6 1341.84   270.1 1342.25   279.8 1342.44   289.6  1341.8
   299.4 1340.23   318.9 1335.99   328.7 1334.41   338.5 1333.35   348.2 1334.06
     358 1338.46   377.6 1352.08   397.1 1365.09   416.7 1378.36   436.2 1391.97
#Mann= 3 , 0 , 0
       0      .1       0   179.4    .045       0   194.4      .1       0
#XS Ineff= 2 , 0
                          272.81         1351.22
Permanent Ineff=
       F       F
Bank Sta=179.4,194.4
XS Rating Curve= 0 ,0
Exp/Cntr=0.3,0.1

Type RM Length L Ch R = 1 ,9637.5  ,116.2,122.3,128.4
XS GIS Cut Line= 2
     1854776.779       368540.08     1855047.101      368659.089
#Sta/Elev= 30
       0  1365.5    19.1 1353.14    28.6 1347.14    38.1  1341.4    47.6 1336.03
    57.2 1331.89    59.7  1331.6    66.7 1330.79    74.7 1331.58    76.2 1331.73
    85.8 1333.21    95.3 1333.99   104.8 1334.19   123.9  1334.2   133.4 1334.09
   142.9 1333.85   152.4 1333.46     162 1332.92   171.5 1332.22     181 1331.27
   190.6 1330.47   200.1  1330.8   209.6 1332.83   219.1 1335.88   228.7 1340.25
   238.2 1345.89   266.8 1364.06   276.3 1370.41   285.8 1377.05   295.4 1383.92
#Mann= 3 , 0 , 0
       0      .1       0    59.7    .045       0    74.7     .08       0
#XS Ineff= 2 , 0
                          117.45         1339.95
Permanent Ineff=
       F       F
Bank Sta=59.7,74.7
XS Rating Curve= 0 ,0
Exp/Cntr=0.3,0.1

Type RM Length L Ch R = 1 ,9515.2  ,595.4,595.1,594.9
XS GIS Cut Line= 2
     1854677.361      368593.389      1854959.64      368823.203
#Sta/Elev= 30
       0 1387.13     9.8 1384.58    19.7 1382.14    29.5 1379.47    39.4 1374.63
    49.2 1368.23    68.9 1353.94    88.5 1339.23    98.4 1332.27   108.2 1327.26
   108.6 1327.22     118 1326.34   123.6 1327.03   127.9 1327.56   137.7  1329.1
   147.6 1329.76   177.1 1329.76   206.6 1329.53   216.4 1329.01   236.1 1326.51
     246 1326.54   255.8 1328.06   265.6 1330.09   275.5 1332.32   285.3 1335.08
   295.1 1338.74     305 1343.17   314.8 1348.38   324.6 1353.99     364  1378.8
#Mann= 3 , 0 , 0
       0      .1       0   108.6    .045       0   123.6     .08       0
Bank Sta=108.6,123.6
XS Rating Curve= 0 ,0
Exp/Cntr=0.3,0.1

Type RM Length L Ch R = 1 ,8920.1  ,159.8,161.5,163.1
XS GIS Cut Line= 3
     1854296.621      369052.374     1854534.213      369241.773
     1854587.085       369269.79
#Sta/Elev= 25
       0 1382.46      49 1351.63    88.2 1327.15      98 1320.97   107.8 1314.59
   117.6 1309.74   118.5 1309.62   127.4 1308.39   133.5 1309.43   137.2 1310.06
     147 1311.95   156.8 1312.76   166.6 1313.07   176.4 1313.26   186.2 1313.19
   205.8 1312.33   215.6 1312.25   284.2  1313.9     294 1314.61   303.8 1316.55
   312.4 1320.33   320.9 1324.78   329.5 1329.43   355.1  1343.5   363.7 1348.11
#Mann= 3 , 0 , 0
       0      .1       0   118.5    .045       0   133.5     .08       0
Bank Sta=118.5,133.5
XS Rating Curve= 0 ,0
Exp/Cntr=0.3,0.1

Type RM Length L Ch R = 1 ,8758.6  ,68.7,68.6,68.7
XS GIS Cut Line= 3
     1854232.805      369200.763     1854449.986      369401.215
      1854567.55      369416.972
#Sta/Elev= 30
       0 1347.43    28.6 1330.05    38.1 1323.77    47.7 1316.04    57.2 1308.56
    66.7 1305.13    76.3 1304.68    81.11305.393    95.3 1307.51   104.9 1308.59
   133.5 1309.21   152.5 1309.13   162.1 1309.35   181.1 1310.26   247.9 1313.09
   276.5 1314.46     286 1315.18   295.6 1316.08   304.7 1318.03   313.8 1321.52
   322.9 1326.04     332 1330.15   341.2 1333.33   350.3 1336.33   359.4 1339.16
   368.5 1341.32   377.7 1342.95   386.8 1344.13   395.9 1345.02   414.2 1346.37
#Mann= 3 , 0 , 0
       0      .1       0    66.7    .045       0    81.1     .08       0
Bank Sta=66.7,81.1
XS Rating Curve= 0 ,0
Exp/Cntr=0.3,0.1

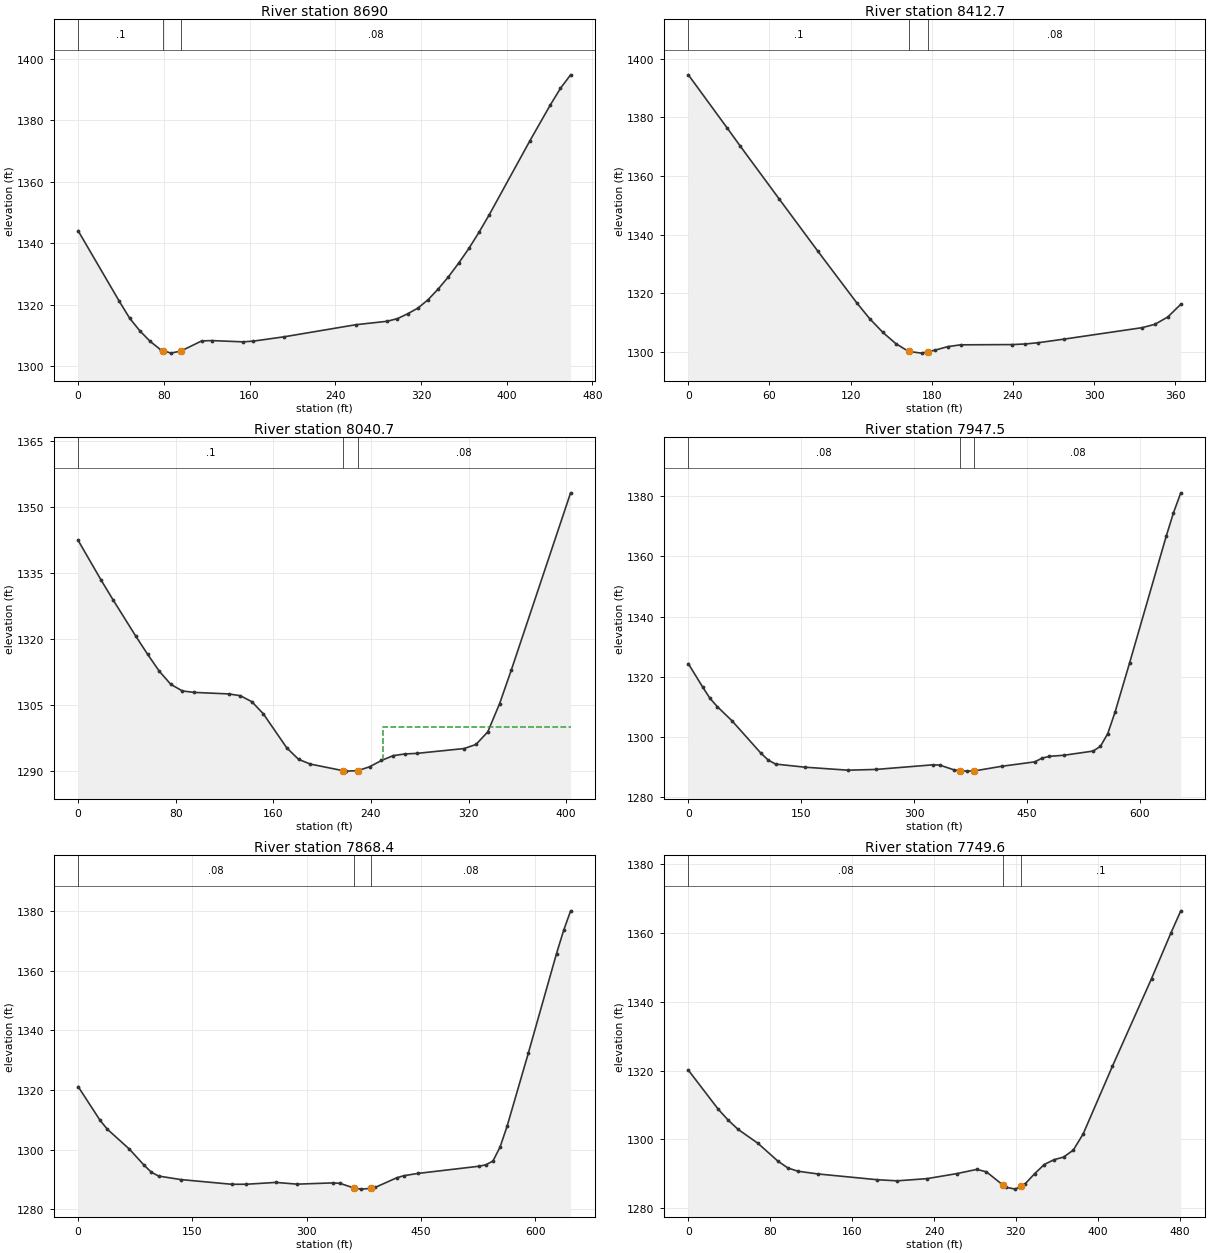
Type RM Length L Ch R = 1 ,8690    ,281.2,277.3,272.9
XS GIS Cut Line= 3
     1854183.311      369247.654     1854417.764      369461.259
     1854447.723      369600.625
#Sta/Elev= 30
       0    1344    38.4 1321.07    48.1 1315.55    57.7 1311.41    67.3    1308
    76.9 1305.33    79.3 1305.05    86.5  1304.2    96.1 1304.91   115.3 1308.17
   124.9 1308.28   153.8 1307.87   163.4  1308.1   192.2 1309.51   259.5 1313.46
   288.3 1314.56     298 1315.42   307.6 1317.01   317.2 1318.86   326.7  1321.6
   336.2 1325.11   345.7 1329.06   355.2 1333.49   364.7 1338.25   374.2 1343.54
   383.7  1349.2   421.7 1373.31   440.7 1384.92   450.2 1390.36   459.7 1394.76
#Mann= 3 , 0 , 0
       0      .1       0    79.3    .045       0    96.1     .08       0
Bank Sta=79.3,96.1
XS Rating Curve= 0 ,0
Exp/Cntr=0.3,0.1

Type RM Length L Ch R = 1 ,8412.7  ,372,372.1,371.3
XS GIS Cut Line= 2
     1853931.833      369428.507     1854239.401      369623.593
#Sta/Elev= 23
       0 1394.51    28.8 1376.32    38.3 1370.25    67.1  1352.2    95.8 1334.32
   124.6 1316.69   134.2 1311.26   143.8 1306.66   153.4 1302.81   162.9 1300.13
   172.5 1299.55   177.3 1300.04   182.1 1300.52   191.7 1301.75   201.3 1302.38
   239.6 1302.47   249.2 1302.68   258.8 1303.11     278 1304.34   335.5 1308.23
     345 1309.37   354.6 1311.89   364.2 1316.22
#Mann= 3 , 0 , 0
       0      .1       0   162.9    .045       0   177.3     .08       0
Bank Sta=162.9,177.3
XS Rating Curve= 0 ,0
Exp/Cntr=0.3,0.1

Type RM Length L Ch R = 1 ,8040.7  ,122.4,93.1,5.7
XS GIS Cut Line= 3
     1853761.576       369676.79     1853864.388      369801.133
     1854070.705      369928.253
#Sta/Elev= 30
       0 1342.42      19  1333.3    28.5 1328.95    47.4 1320.56    56.9 1316.53
    66.4  1312.7    75.9 1309.68    85.4 1308.17    94.9 1307.84   123.4 1307.49
   132.9 1307.09   142.4 1305.71   151.8 1302.96     171 1295.22   180.7  1292.6
   190.4 1291.52   216.91290.036   219.5 1289.92   229.2 1290.02   238.9 1290.91
   248.6 1292.34   258.3 1293.45     268 1293.83   277.7 1293.96   316.4 1295.06
   326.1 1295.98   335.8 1298.86   345.5 1305.29   355.2 1313.02   403.7 1353.25
#Mann= 3 , 0 , 0
       0      .1       0   216.9    .045       0   229.2     .08       0
#XS Ineff= 2 , 0
       0                     250       0    1300
Permanent Ineff=
       F       F
Bank Sta=216.9,229.2
XS Rating Curve= 0 ,0
Exp/Cntr=0.3,0.1

Type RM Length L Ch R = 1 ,7947.5  ,98.2,79.2,132.7
XS GIS Cut Line= 6
     1853585.829      369849.764      1853735.96      369999.785
     1853813.067      369946.643     1853888.089      369891.937
     1853932.374      369849.214     1854079.042      369976.185
#Sta/Elev= 30
       0 1324.36    19.3  1316.5    28.9  1312.8    38.6 1310.06    57.9 1305.42
    96.5  1294.6   106.1 1292.35   115.8 1291.01   154.4 1289.98   212.2 1288.97
   249.7 1289.23   324.5 1290.75   333.7 1290.69   352.3 1289.14   361.2 1288.76
   370.9 1288.66   380.2 1288.74   416.3 1290.27   460.3 1291.74     470 1292.98
   479.7 1293.57   499.1 1293.94   537.9 1295.33   547.6 1296.92   557.3 1301.16
     567 1308.31   586.4 1324.73   634.9  1366.7   644.6 1374.55   654.3 1381.15
#Mann= 3 , 0 , 0
       0     .08       0   361.2    .045       0   380.2     .08       0
Bank Sta=361.2,380.2
XS Rating Curve= 0 ,0
Exp/Cntr=0.3,0.1

Type RM Length L Ch R = 1 ,7868.4  ,82.7,118.8,140.6
XS GIS Cut Line= 6
     1853580.272      369869.214     1853759.406      370056.921
     1853836.513      370003.778     1853911.535      369949.072
     1853955.819       369906.35     1854058.897      369999.803
#Sta/Elev= 30
       0 1321.12    28.8 1309.81    38.4 1306.82    67.3 1300.17    86.5 1294.81
    96.1 1292.44   105.7 1291.15   134.5 1289.98   201.8 1288.39     221 1288.41
   259.5 1289.02   287.6 1288.44   334.4 1288.86   343.8 1288.71   362.4 1287.12
   371.7 1286.77   384.51287.039   390.2 1287.37   418.1 1290.55   427.4 1291.25
     446 1292.03     526 1294.43   535.3 1294.92   544.6 1296.19   553.9 1300.82
   563.2 1307.84     591 1332.26   628.1 1365.69   637.4 1373.42   646.6 1380.01
#Mann= 3 , 0 , 0
       0     .08       0   362.4    .045       0   384.5     .08       0
Bank Sta=362.4,384.5
XS Rating Curve= 0 ,0
Exp/Cntr=0.3,0.1

Type RM Length L Ch R = 1 ,7749.6  ,51.7,72.4,92.2
XS GIS Cut Line= 4
     1853576.104      369878.245     1853765.751      370086.641
       1853850.5      370089.418      1853935.25      370166.525
#Sta/Elev= 30
       0 1320.13    29.2 1308.78    38.9 1305.61    48.6 1302.92      68 1298.88
    87.4 1293.72    97.2 1291.72   106.9 1290.77   126.3 1289.98   184.6 1288.29
     204 1287.97   233.2 1288.61   262.3 1290.07   281.8 1291.29   291.2 1290.59
   307.8 1286.64     310 1286.12   319.5 1285.56   324.81286.408   328.9 1287.06
   338.3 1290.04   347.7  1292.7   357.1  1294.1   366.6 1294.87   376.1 1296.91
   385.7 1301.59   414.3 1321.27   452.5 1346.72   471.6 1360.09   481.1 1366.42
#Mann= 3 , 0 , 0
       0     .08       0   307.8    .045       0   324.8      .1       0
Bank Sta=307.8,324.8
XS Rating Curve= 0 ,0
Exp/Cntr=0.3,0.1

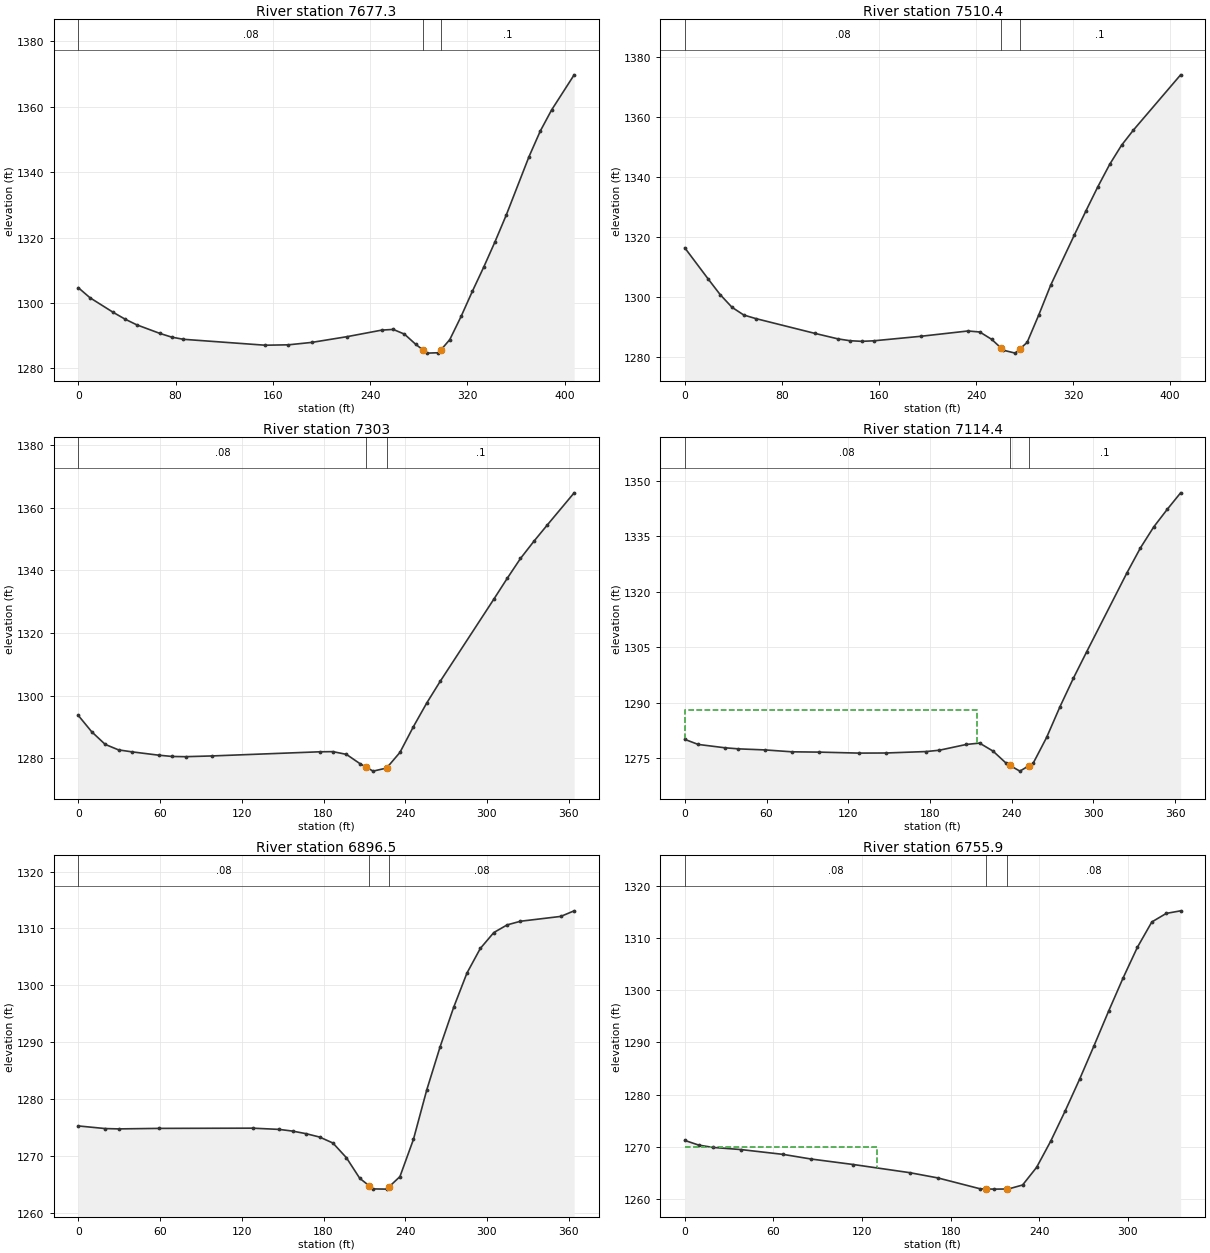
Type RM Length L Ch R = 1 ,7677.3  ,160.3,166.8,173.3
XS GIS Cut Line= 3
     1853552.916      369958.826     1853744.385      370119.029
     1853839.469      370245.369
#Sta/Elev= 30
       0 1304.68     9.6 1301.61    28.8 1297.12    38.4 1295.08      48 1293.34
    67.2 1290.69    76.8 1289.57    86.4 1288.91   153.6  1287.1   172.8 1287.22
     192 1287.96   220.8  1289.7   249.6 1291.72     259 1291.93   268.2 1290.49
   277.6 1287.34   283.3 1285.71   286.9 1284.68   296.2  1284.8   298.3 1285.71
   305.5 1288.81   314.8 1295.89   324.1  1303.6   333.4 1310.96   342.7 1318.73
     352 1326.94   370.6  1344.7   379.9 1352.55   389.2    1359   407.8 1369.77
#Mann= 3 , 0 , 0
       0     .08       0   283.3    .045       0   298.3      .1       0
Bank Sta=283.3,298.3
XS Rating Curve= 0 ,0
Exp/Cntr=0.3,0.1

Type RM Length L Ch R = 1 ,7510.4  ,218.8,207.4,195.8
XS GIS Cut Line= 3
     1853472.162      370014.834     1853612.835      370201.088
     1853674.054      370365.202
#Sta/Elev= 29
       0 1316.29    19.4 1305.84    29.2 1300.68    38.9 1296.48    48.6 1293.91
    58.4 1292.73     107 1287.81   126.4 1285.94   136.2 1285.34   145.9 1285.14
   155.6 1285.31   194.5 1286.82   233.4 1288.59   243.1 1288.25   252.9  1285.8
   260.9 1282.81   262.6 1282.17   272.3 1281.21   275.9 1282.52   282.1 1284.78
   291.8 1294.03   301.5 1303.84     321 1320.55   330.7 1328.71   340.4 1336.66
   350.2 1344.14   359.9 1350.46   369.6 1355.48   408.6 1373.93
#Mann= 3 , 0 , 0
       0     .08       0   260.9    .045       0   275.9      .1       0
Bank Sta=260.9,275.9
XS Rating Curve= 0 ,0
Exp/Cntr=0.3,0.1

Type RM Length L Ch R = 1 ,7303    ,187.3,188.6,189.5
XS GIS Cut Line= 2
     1853302.129      370222.214     1853579.296      370458.168
#Sta/Elev= 26
       0 1293.67     9.8 1288.48    19.7 1284.45    29.5 1282.69    39.4 1282.06
      59    1281    68.9 1280.59    78.7 1280.52    98.4 1280.76   177.1 1282.08
   186.9 1282.13   196.8 1281.26   206.6 1278.34   211.4 1277.15   216.4 1275.91
   226.3 1276.89   236.1 1281.88     246 1290.11   255.8 1297.67   265.6 1304.53
     305 1330.77   314.8  1337.4   324.6 1343.78   334.5  1349.3   344.3 1354.48
     364 1364.73
#Mann= 3 , 0 , 0
       0     .08       0   211.4    .045       0   226.3      .1       0
Bank Sta=211.4,226.3
XS Rating Curve= 0 ,0
Exp/Cntr=0.3,0.1

Type RM Length L Ch R = 1 ,7114.4  ,205.2,217.9,230.2
XS GIS Cut Line= 2
      1853185.84      370352.122     1853450.722      370601.788
#Sta/Elev= 28
       0 1280.04     9.8 1278.67    29.5 1277.76    39.4 1277.47      59 1277.18
    78.7 1276.67    98.4 1276.59   127.9 1276.32   147.6 1276.35   177.1 1276.74
   186.9  1277.1   206.6 1278.66   216.4 1279.03   226.3 1276.86   236.1 1273.52
   238.6 1272.99     246 1271.44   252.6  1272.9   255.8 1273.61   265.6 1280.55
   275.5 1288.94   285.3 1296.62   295.1 1303.81   324.6 1325.14   334.5 1331.89
   344.3 1337.59   354.2 1342.34     364  1346.8
#Mann= 3 , 0 , 0
       0     .08       0   238.6    .045       0   252.6      .1       0
#XS Ineff= 2 , 0
          214.35 1287.93
Permanent Ineff=
       F       F
Bank Sta=238.6,252.6
XS Rating Curve= 0 ,0
Exp/Cntr=0.3,0.1

Type RM Length L Ch R = 1 ,6896.5  ,145.8,140.6,135.3
XS GIS Cut Line= 2
     1853140.622      370445.818     1853235.445       370797.25
#Sta/Elev= 28
       0 1275.31    19.7 1274.85    29.5 1274.79      59 1274.88   127.9 1274.92
   147.6  1274.7   157.4  1274.4   167.2 1273.95   177.1 1273.36   186.9 1272.31
   196.8 1269.73   206.6 1266.11   213.3 1264.84   216.4 1264.25   226.3 1264.21
   228.3 1264.66   236.1 1266.41     246 1272.94   255.8 1281.65   265.6 1289.22
   275.5 1296.12   285.3 1302.17   295.1 1306.49     305 1309.28   314.8 1310.63
   324.6 1311.27   354.2 1312.12     364  1313.1
#Mann= 3 , 0 , 0
       0     .08       0   213.3    .045       0   228.3     .08       0
Bank Sta=213.3,228.3
XS Rating Curve= 0 ,0
Exp/Cntr=0.3,0.1

Type RM Length L Ch R = 1 ,6755.9  ,61.3,85.5,108.4
XS GIS Cut Line= 4
     1852996.185      370534.971     1853017.444      370617.784
     1853094.353      370760.671      1853160.13      370819.085
#Sta/Elev= 26
       0 1271.23     9.5 1270.33      19 1269.89      38 1269.48    66.5 1268.56
    85.5 1267.67   114.1 1266.62   152.3 1265.06   171.4 1264.05     200 1261.97
   204.1 1261.94   209.6 1261.91   218.11261.937   219.1 1261.94   228.7  1262.7
   238.2 1266.08   247.8 1271.12   257.5 1276.85   267.3 1282.94   277.1 1289.37
   286.9 1295.94   296.6 1302.22   306.4 1308.17   316.2 1313.03     326 1314.67
   335.7 1315.16
#Mann= 3 , 0 , 0
       0     .08       0   204.1    .045       0   218.1     .08       0
#XS Ineff= 2 , 0
       0     130    1270               0
Permanent Ineff=
       F       F
Bank Sta=204.1,218.1
XS Rating Curve= 0 ,0
Exp/Cntr=0.3,0.1

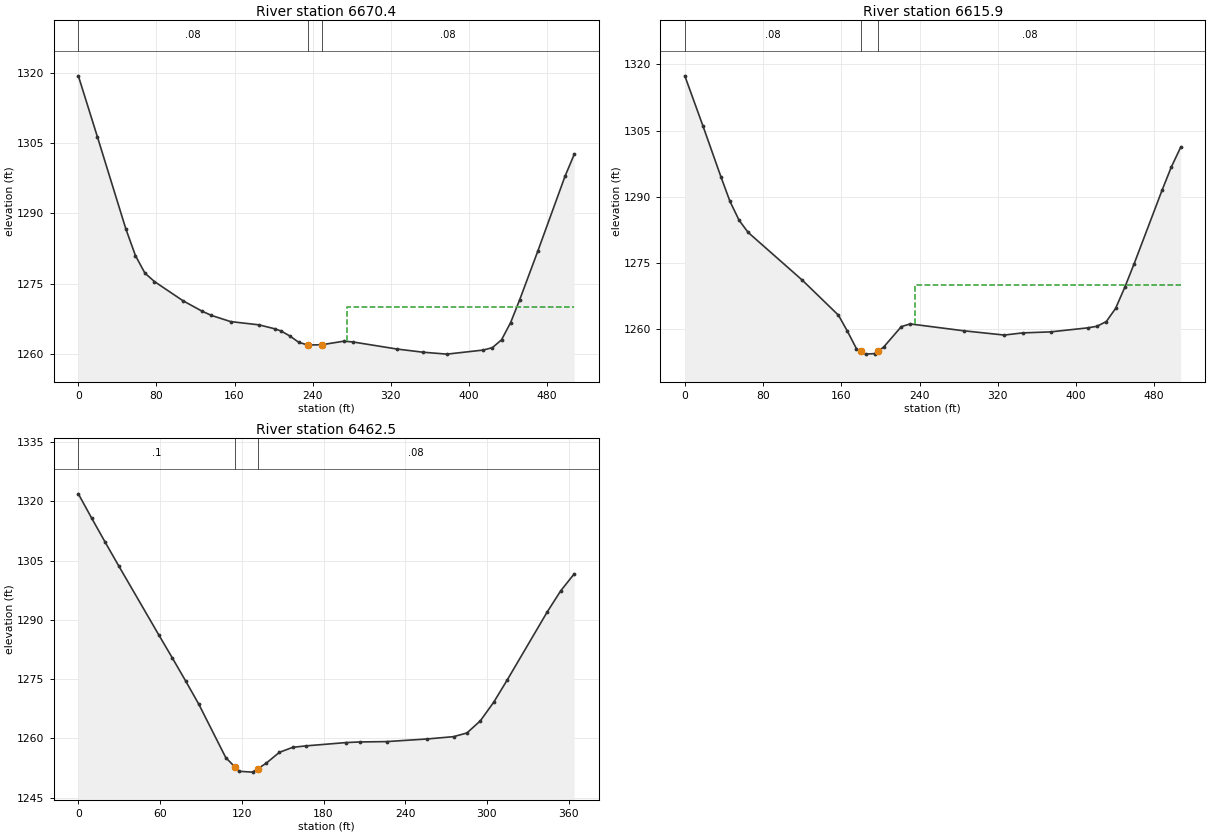
Type RM Length L Ch R = 1 ,6670.4  ,54.4,54.5,60.9
XS GIS Cut Line= 6
     1852900.321      370510.659     1853026.222      370659.422
     1852970.714      370758.392     1852955.031      370791.172
     1852944.198      370822.208     1853051.872       370895.58
#Sta/Elev= 30
       0  1319.3    19.5 1306.32    48.7 1286.65    58.5 1280.98    68.2 1277.24
      78 1275.44   107.2 1271.35   126.7 1269.13   136.4 1268.22   155.9 1266.91
   185.1 1266.21   201.2 1265.37   207.6 1264.91   216.8 1263.82     226 1262.46
   235.2 1261.92   249.21261.965     272 1262.73   281.1 1262.57   326.6 1261.05
     353 1260.38   377.6 1259.97   414.9 1260.84   424.2 1261.36   433.5 1263.02
   442.8 1266.69   452.1 1271.56   470.7 1281.95   498.6 1297.92   507.9 1302.53
#Mann= 3 , 0 , 0
       0     .08       0   235.2    .045       0   249.2     .08       0
#XS Ineff= 2 , 0
       0                     275       0    1270
Permanent Ineff=
       F       F
Bank Sta=235.2,249.2
XS Rating Curve= 0 ,0
Exp/Cntr=0.3,0.1

Type RM Length L Ch R = 1 ,6615.9  ,187.7,153.4,112.1
XS GIS Cut Line= 6
     1852874.756      370532.534     1852971.092      370644.771
     1852922.522      370733.125     1852906.838      370765.904
     1852892.533      370804.842     1853043.623      370903.395
#Sta/Elev= 30
       0 1317.42    18.5 1306.11      37 1294.52    46.2 1288.98    55.5 1284.72
    64.7 1281.97   120.2 1271.13   157.1 1263.21   166.3 1259.57   175.5 1255.63
   179.8 1255.06   184.8 1254.39     194 1254.51     1981255.139   203.2 1255.95
   221.4 1260.62   230.5 1261.23   285.1 1259.68   326.6 1258.71   345.6  1259.2
   374.1 1259.43     412 1260.34   421.5  1260.7     431 1261.77   440.5 1264.74
     450 1269.58   459.5 1274.88     488  1291.5   497.5 1296.78     507 1301.22
#Mann= 3 , 0 , 0
       0     .08       0   179.8    .045       0     198     .08       0
#XS Ineff= 2 , 0
       0                     235       0    1270
Permanent Ineff=
       F       F
Bank Sta=179.8,198
XS Rating Curve= 0 ,0
Exp/Cntr=0.3,0.1

Type RM Length L Ch R = 1 ,6462.5  ,184.2,182.7,180.9
XS GIS Cut Line= 2
     1852737.696      370708.806     1853042.356         370908.
#Sta/Elev= 29
       0 1321.94     9.8 1315.78    19.7  1309.7    29.5 1303.79      59 1286.26
    68.9 1280.46    78.7 1274.61    88.5 1268.64   108.2 1255.18   114.9 1252.79
     118 1251.69   127.9 1251.48   131.91252.379   137.7 1253.68   147.6 1256.49
   157.4 1257.76   167.2 1258.13   196.8 1258.97   206.6 1259.12   226.3 1259.21
   255.8 1259.87   275.5 1260.46   285.3  1261.4   295.1 1264.46     305 1269.21
   314.8 1274.78   344.3 1292.08   354.2 1297.42     364 1301.66
#Mann= 3 , 0 , 0
       0      .1       0   114.9    .045       0   131.9     .08       0
Bank Sta=114.9,131.9
XS Rating Curve= 0 ,0
Exp/Cntr=0.3,0.1