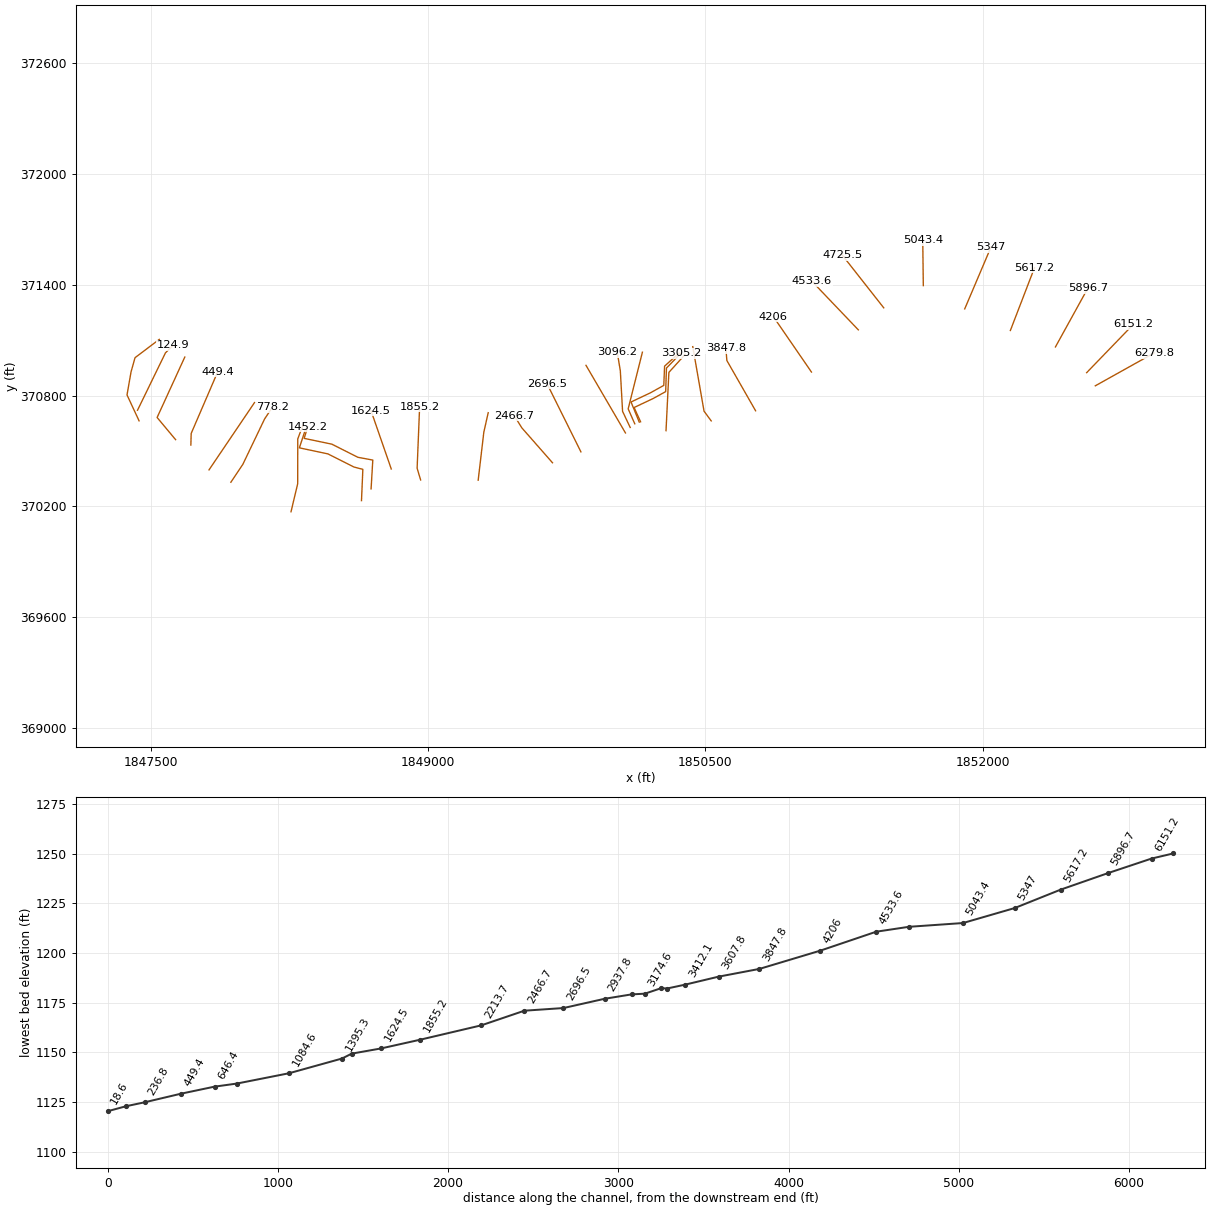
HEC-RAS study CABINCK.prj: CABINCK

--- CABINCK.g01 (geometry) --- (continued)

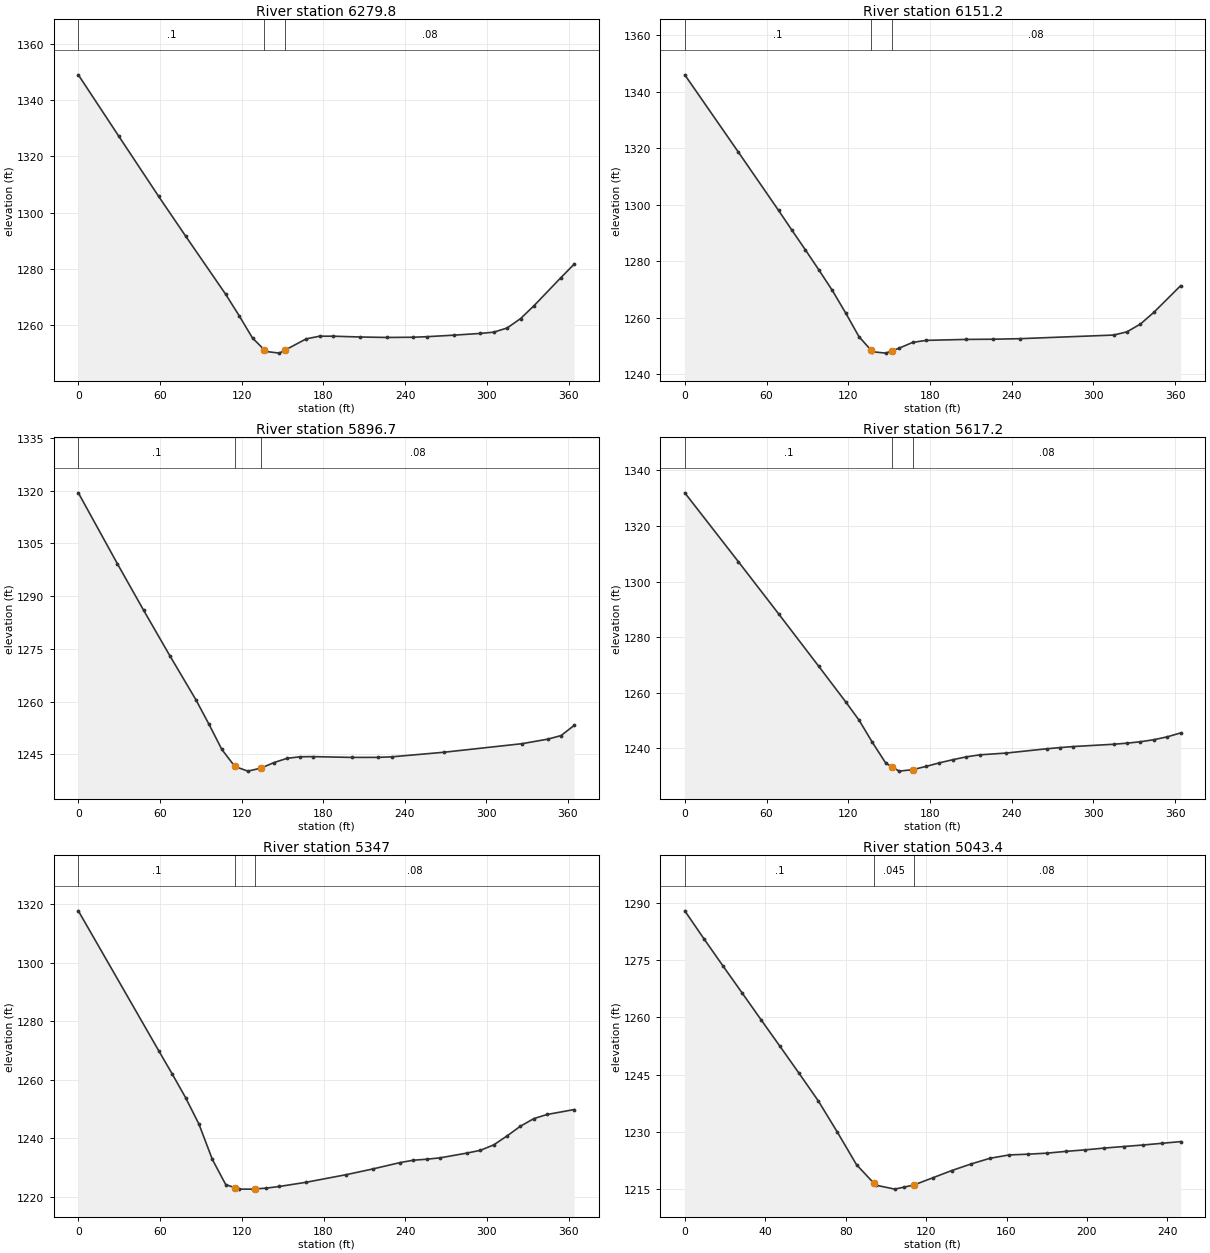
Type RM Length L Ch R = 1 ,6279.8  ,121.9,128.6,135.2
XS GIS Cut Line= 2
     1852610.004       370852.72     1852927.903      371030.193
#Sta/Elev= 26
       0 1349.01    29.5 1327.34      59 1305.79    78.7 1291.75   108.2    1271
   118.1 1263.38   127.9 1255.45   136.7  1251.2   137.8 1250.67   147.6 1250.08
   151.7 1251.13   167.3 1255.14   177.1  1256.1     187  1256.1   206.6 1255.82
   226.3 1255.65     246 1255.73   255.8 1255.92   275.5 1256.46   295.2 1257.08
     305 1257.53   314.9 1259.02   324.7 1262.34   334.6 1266.93   354.2 1276.83
   364.1 1281.72
#Mann= 3 , 0 , 0
       0      .1       0   136.7    .045       0   151.7     .08       0
Bank Sta=136.7,151.7
XS Rating Curve= 0 ,0
Exp/Cntr=0.3,0.1

Type RM Length L Ch R = 1 ,6151.2  ,248.4,254.6,260.3
XS GIS Cut Line= 2
     1852563.244      370923.799     1852816.283      371185.577
#Sta/Elev= 24
       0 1345.91    39.4 1318.54    68.9 1297.93    78.7 1290.94    88.6 1283.98
    98.4 1276.96   108.2 1269.77   118.1 1261.72   127.9 1253.32   136.8 1248.52
   137.8 1247.98   147.6 1247.49   151.8 1248.24   157.4 1249.25   167.3 1251.28
   177.1    1252   206.6 1252.34   226.3 1252.41     246  1252.6   314.9 1253.88
   324.7 1255.02   334.6 1257.79   344.4  1261.9   364.1 1271.34
#Mann= 3 , 0 , 0
       0      .1       0   136.8    .045       0   151.8     .08       0
Bank Sta=136.8,151.8
XS Rating Curve= 0 ,0
Exp/Cntr=0.3,0.1

Type RM Length L Ch R = 1 ,5896.7  ,276.2,279.5,282.4
XS GIS Cut Line= 2
     1852394.317      371062.942     1852570.481      371382.151
#Sta/Elev= 22
       0 1319.35    28.8 1299.13      48 1285.96    67.2 1273.09    86.4 1260.54
      96 1253.59   105.5 1246.39   115.1 1241.53   124.7 1240.21   134.3 1241.07
   143.9 1242.65   153.5 1243.85   163.1  1244.3   172.7 1244.33   201.5 1244.11
   220.7 1244.13   230.3 1244.27   268.6 1245.57   326.2 1248.01   345.4 1249.32
     355 1250.33   364.6 1253.22
#Mann= 3 , 0 , 0
       0      .1       0   115.1    .045       0   134.3     .08       0
Bank Sta=115.1,134.3
XS Rating Curve= 0 ,0
Exp/Cntr=0.3,0.1

Type RM Length L Ch R = 1 ,5617.2  ,271,270.1,269.4
XS GIS Cut Line= 2
     1852150.486      371151.797      1852281.16      371491.533
#Sta/Elev= 26
       0 1331.89    39.4  1307.1    68.9 1288.38    98.4  1269.5     118 1256.84
   127.9  1250.2   137.7 1242.21   147.6  1234.7   152.21233.369   157.4 1231.86
   167.2 1232.38   177.1 1233.55   186.9 1234.84   196.8 1235.97   206.6 1236.99
   216.4 1237.71   236.1 1238.36   265.6 1239.89   275.5 1240.32   285.3  1240.7
   314.8 1241.52   324.6 1241.91   334.5 1242.42   344.3 1243.15   354.2 1244.19
     364 1245.59
#Mann= 3 , 0 , 0
       0      .1       0   152.2    .045       0   167.2     .08       0
Bank Sta=152.2,167.2
XS Rating Curve= 0 ,0
Exp/Cntr=0.3,0.1

Type RM Length L Ch R = 1 ,5347    ,293.8,303.6,312.6
XS GIS Cut Line= 2
     1851903.571      371268.796     1852045.983      371603.781
#Sta/Elev= 28
       0 1317.68      59  1269.9    68.9 1261.96    78.7 1253.89    88.5 1244.86
    98.4 1232.74   108.2 1224.16     1151223.076     118  1222.6   127.9  1222.6
     130 1222.67   137.7 1222.93   147.6 1223.51   167.2 1224.94   196.8 1227.55
   216.4 1229.52   236.1 1231.66     246 1232.48   255.8 1232.82   265.6 1233.29
   285.3 1234.92   295.1 1235.85     305 1237.73   314.8  1240.8   324.6 1244.11
   334.5 1246.72   344.3 1248.12     364 1249.78
#Mann= 3 , 0 , 0
       0      .1       0     115    .045       0     130     .08       0
Bank Sta=115,130
XS Rating Curve= 0 ,0
Exp/Cntr=0.3,0.1

Type RM Length L Ch R = 1 ,5043.4  ,303,317.9,332.6
XS GIS Cut Line= 2
     1851679.587      371394.973     1851676.586      371641.593
#Sta/Elev= 29
       0 1287.91     9.5 1280.61      19 1273.48    28.5 1266.43    37.9 1259.42
    47.4 1252.41    56.9 1245.34    66.4 1238.16    75.9 1229.97    85.4 1221.47
      94 1216.63    94.9 1216.12   104.4 1215.07     109 1215.59   113.8 1216.13
   123.3 1218.03   132.8 1219.94   142.3 1221.64   151.8 1223.15   161.3 1224.02
   170.8 1224.22   180.2 1224.49   189.7 1224.96   199.2 1225.35   208.7 1225.82
   218.2 1226.22   227.7 1226.61   237.2 1227.06   246.6 1227.51
#Mann= 3 , 0 , 0
       0      .1       0      94    .045       0   113.8     .08       0
Bank Sta=94,113.8
XS Rating Curve= 0 ,0
Exp/Cntr=0.3,0.1

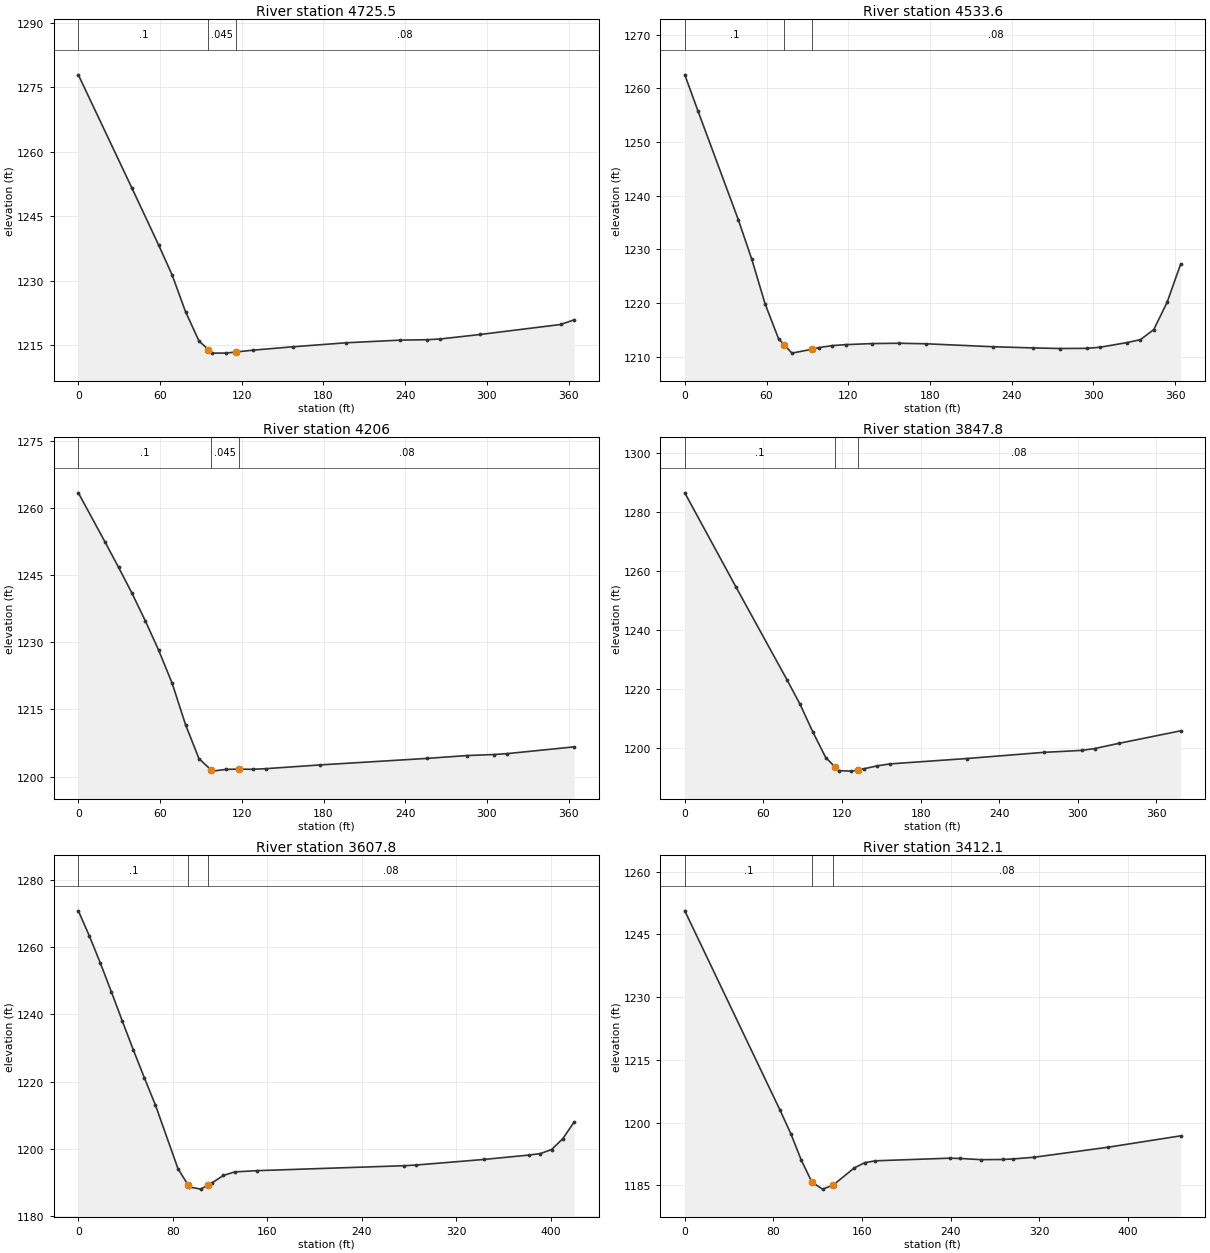
Type RM Length L Ch R = 1 ,4725.5  ,189.7,191.9,194.1
XS GIS Cut Line= 2
     1851465.584      371274.569     1851240.483      371560.726
#Sta/Elev= 19
       0 1277.88    39.4 1251.52      59 1238.29    68.9 1231.34    78.7 1222.82
    88.6 1215.99    95.51214.005    98.4 1213.17   108.2 1213.18   116.11213.443
   127.9 1213.85   157.4 1214.64   196.8 1215.58   236.2 1216.19   255.8 1216.29
   265.7 1216.46   295.2 1217.51   354.2 1219.83   364.1 1220.92
#Mann= 3 , 0 , 0
       0      .1       0    95.5    .045       0   116.1     .08       0
Bank Sta=95.5,116.1
XS Rating Curve= 0 ,0
Exp/Cntr=0.3,0.1

Type RM Length L Ch R = 1 ,4533.6  ,331.1,327.6,323.9
XS GIS Cut Line= 2
     1851328.054      371155.439     1851076.526      371418.669
#Sta/Elev= 25
       0 1262.51     9.8  1255.7    39.4 1235.47    49.2 1228.17      59 1219.86
    68.9 1213.36    73.2  1212.2    78.7 1210.71    93.21211.427    98.4 1211.74
   108.2 1212.11   118.1 1212.29   137.8 1212.49   157.4 1212.55   177.1 1212.45
   226.3  1211.9   255.8 1211.68   275.5 1211.57   295.2  1211.6     305 1211.81
   324.7 1212.67   334.6 1213.22   344.4  1215.1   354.2 1220.19   364.1 1227.28
#Mann= 3 , 0 , 0
       0      .1       0    73.2    .045       0    93.2     .08       0
Bank Sta=73.2,93.2
XS Rating Curve= 0 ,0
Exp/Cntr=0.3,0.1

Type RM Length L Ch R = 1 ,4206    ,360.1,358.2,356.4
XS GIS Cut Line= 2
     1851074.517      370927.245     1850868.265      371227.172
#Sta/Elev= 21
       0 1263.38    19.7 1252.34    29.5 1246.76    39.4 1240.94    49.2 1234.77
      59  1228.2    68.9 1220.83    78.7  1211.6    88.5 1204.03    97.71201.409
    98.4 1201.21   108.2  1201.6     118 1201.66   127.9 1201.62   137.7 1201.76
   177.1 1202.59   255.8 1204.05   285.3 1204.69     305 1204.92   314.8 1205.12
     364 1206.63
#Mann= 3 , 0 , 0
       0      .1       0    97.7    .045       0     118     .08       0
Bank Sta=97.7,118
XS Rating Curve= 0 ,0
Exp/Cntr=0.3,0.1

Type RM Length L Ch R = 1 ,3847.8  ,247.7,240,232.1
XS GIS Cut Line= 3
     1850772.343        370717.6     1850617.005      370989.337
     1850611.416      371054.617
#Sta/Elev= 19
       0 1286.54    39.1 1254.53    78.2 1222.88      88  1214.7    97.8 1205.27
   107.6 1196.62     1151193.266   117.4 1192.18   127.2 1192.01     1321192.412
   136.9 1192.82   146.7 1193.79   156.5 1194.46   215.2 1196.29   273.9 1198.38
   303.2 1199.06     313 1199.69   331.7 1201.48   378.5  1205.7
#Mann= 3 , 0 , 0
       0      .1       0     115    .045       0     132     .08       0
Bank Sta=115,132
XS Rating Curve= 0 ,0
Exp/Cntr=0.3,0.1

Type RM Length L Ch R = 1 ,3607.8  ,200.7,195.7,190.7
XS GIS Cut Line= 3
     1850532.118      370662.871     1850493.409      370715.469
      1850432.47      371064.601
#Sta/Elev= 25
       0 1270.78     9.3 1263.35    18.7 1255.21      28 1246.69    37.3 1237.98
    46.6 1229.44      56 1221.09    65.3 1213.05    84.5 1194.05      931189.318
      94 1188.76   103.6 1188.11     1101189.356   113.2 1189.98   122.8 1192.18
   132.4 1193.23   151.5  1193.6     276 1195.07   285.6 1195.26   343.1 1196.92
   381.4 1198.23     391 1198.66   400.6 1199.88   410.1 1203.11   419.7 1208.06
#Mann= 3 , 0 , 0
       0      .1       0      93    .045       0     110     .08       0
Bank Sta=93,110
XS Rating Curve= 0 ,0
Exp/Cntr=0.3,0.1

Type RM Length L Ch R = 1 ,3412.1  ,132.9,106.9,81.3
XS GIS Cut Line= 3
     1850287.702      370610.066     1850303.251      370925.402
     1850391.902      371023.361
#Sta/Elev= 18
       0 1250.64    86.1 1202.94    95.7  1197.4   105.2 1191.05   114.8 1185.78
   124.4 1184.11   133.9 1185.06   153.1 1189.19   162.6 1190.44   172.2 1190.88
   239.2 1191.51   248.8 1191.44   267.9 1191.15     287  1191.2   296.6 1191.33
   315.7 1191.74   381.8 1194.11   447.8 1196.85
#Mann= 3 , 0 , 0
       0      .1       0   114.8    .045       0   133.9     .08       0
Bank Sta=114.8,133.9
XS Rating Curve= 0 ,0
Exp/Cntr=0.3,0.1

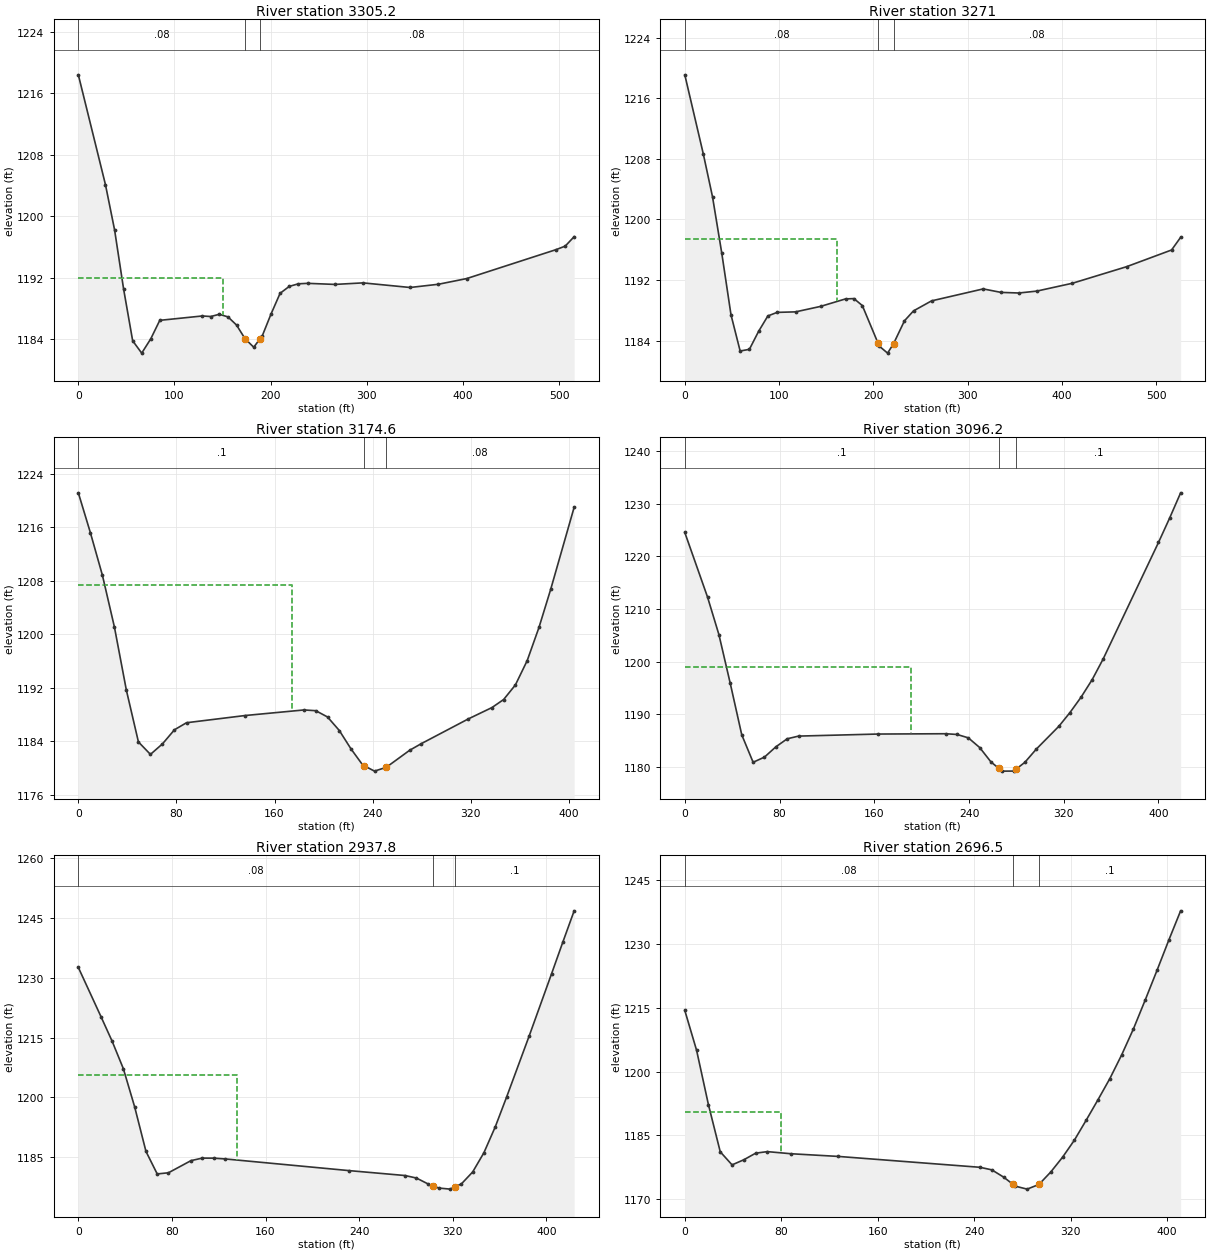
Type RM Length L Ch R = 1 ,3305.2  ,34.4,34.2,34.3
XS GIS Cut Line= 6
     1850150.299      370658.133      1850114.96      370735.158
      1850219.16      370784.477     1850285.848      370821.293
     1850290.104      370948.586     1850367.821      371028.905
#Sta/Elev= 30
       0  1218.4    28.2  1204.1    37.7  1198.2    47.1 1190.48    56.5 1183.76
    65.9 1182.15    75.3 1184.01    84.7 1186.42   128.9 1186.99   137.8 1186.92
   146.6 1187.21   155.6 1186.87   164.5 1185.81   173.4 1184.02   182.4 1182.92
   188.8 1183.99   191.3 1184.41   200.3 1187.22   209.8 1189.94   219.3 1190.84
   228.8 1191.18   238.4 1191.24   266.9  1191.1     296  1191.3     345  1190.7
   374.4 1191.12   403.8 1191.86     497 1195.64   506.3 1196.09   515.6 1197.32
#Mann= 3 , 0 , 0
       0     .08       0   173.4    .045       0   188.8     .08       0
#XS Ineff= 2 , 0
       0     150    1192               0
Permanent Ineff=
       F       F
Bank Sta=173.4,188.8
XS Rating Curve= 0 ,0
Exp/Cntr=0.3,0.1

Type RM Length L Ch R = 1 ,3271    ,74.2,96.4,117.3
XS GIS Cut Line= 6
     1850142.918      370656.396       1850098.5      370765.156
       1850202.7      370814.476     1850275.682      370854.973
     1850279.933      370959.032     1850357.835      371029.774
#Sta/Elev= 30
       0 1219.09    19.6 1208.66    29.4 1202.98    39.2 1195.55      49  1187.4
    58.7 1182.62    68.5 1182.84    78.3 1185.22    88.1 1187.25    97.9 1187.72
   117.5 1187.79     144 1188.51   170.5  1189.5   179.4 1189.54   188.3 1188.62
     2051183.643   206.2 1183.27   215.1 1182.34   221.5 1183.61     233 1186.61
   242.6 1187.92   261.7 1189.24   316.5 1190.82   335.4 1190.36   354.4 1190.28
   373.3 1190.53   411.2 1191.57   468.5 1193.75   516.3 1195.96   525.9 1197.63
#Mann= 3 , 0 , 0
       0     .08       0     205    .045       0   221.5     .08       0
#XS Ineff= 2 , 0
           161.4 1197.38
Permanent Ineff=
       F       F
Bank Sta=205,221.5
XS Rating Curve= 0 ,0
Exp/Cntr=0.3,0.1

Type RM Length L Ch R = 1 ,3174.6  ,71.5,78.3,85.2
XS GIS Cut Line= 3
     1850118.604      370647.279     1850083.004      370728.034
     1850159.969      371034.583
#Sta/Elev= 30
       0 1221.13     9.8 1215.19    19.6 1208.84    29.4  1201.1    39.2 1191.62
      49 1183.91    58.8 1182.05    68.6 1183.62    78.4 1185.73    88.2 1186.78
   136.1 1187.86     184 1188.69   193.6 1188.58   203.2 1187.64   212.8 1185.62
   222.3 1182.88   231.9 1180.46   233.1 1180.35   241.5 1179.55   251.1 1180.12
   270.2 1182.67   279.8 1183.67   318.1 1187.36   337.3 1189.05   346.8 1190.25
   356.4 1192.43     366 1196.06   375.6 1201.01   385.2 1206.73   404.3 1218.98
#Mann= 3 , 0 , 0
       0      .1       0   233.1    .045       0   251.1     .08       0
#XS Ineff= 2 , 0
          174.02 1207.38
Permanent Ineff=
       F       F
Bank Sta=233.1,251.1
XS Rating Curve= 0 ,0
Exp/Cntr=0.3,0.1

Type RM Length L Ch R = 1 ,3096.2  ,147.4,158.5,167.4
XS GIS Cut Line= 4
     1850093.886      370627.408     1850052.749      370714.272
     1850040.589      370933.727     1850023.731      371035.176
#Sta/Elev= 30
       0 1224.56    19.2 1212.28    28.8 1205.15    38.4 1195.86    48.1 1186.09
    57.7 1180.87    67.3 1181.86    76.9 1183.81    86.5 1185.34    96.1 1185.85
     163 1186.24   220.3  1186.3   229.9 1186.16   239.4 1185.52     249 1183.68
   258.6 1180.92     2651179.753   268.1 1179.19   277.7  1179.2     2801179.606
   287.2 1180.87   296.8 1183.37   315.9 1187.72   325.2 1190.31   334.6 1193.24
     344 1196.58   353.3 1200.52     400 1222.66   409.4 1227.29   418.7  1232.1
#Mann= 3 , 0 , 0
       0      .1       0     265    .045       0     280      .1       0
#XS Ineff= 2 , 0
          190.97 1198.95
Permanent Ineff=
       F       F
Bank Sta=265,280
XS Rating Curve= 0 ,0
Exp/Cntr=0.3,0.1

Type RM Length L Ch R = 1 ,2937.8  ,242.7,241.2,241.6
XS GIS Cut Line= 2
     1850068.309      370597.736     1849854.746      370963.638
#Sta/Elev= 29
       0 1232.57    19.3 1220.27    28.9 1214.06    38.5 1207.16    48.1 1197.64
    57.8 1186.44    67.4 1180.79      77 1181.08    96.3 1184.13   105.9 1184.76
   115.6 1184.75   125.2 1184.56   231.1 1181.63   279.2 1180.39   288.9 1179.76
   298.5 1178.33     3031177.822   308.1 1177.25   317.8 1176.98     3221177.559
   327.4 1178.31     337 1181.29   346.6 1186.12   356.3 1192.61   365.9 1200.01
   385.2 1215.34   404.4 1230.99     414 1238.91   423.7 1246.77
#Mann= 3 , 0 , 0
       0     .08       0     303    .045       0     322      .1       0
#XS Ineff= 2 , 0
          135.52  1205.6
Permanent Ineff=
       F       F
Bank Sta=303,322
XS Rating Curve= 0 ,0
Exp/Cntr=0.3,0.1

Type RM Length L Ch R = 1 ,2696.5  ,223.7,229.8,235.4
XS GIS Cut Line= 2
     1849827.328      370495.441     1849644.291      370863.682
#Sta/Elev= 29
       0  1214.4     9.8 1204.99    19.6 1192.22    29.4 1181.12    39.2 1178.04
      49 1179.25    58.8  1180.8    68.5 1181.16    88.1 1180.66   127.3 1180.03
   244.8 1177.47   254.6 1176.87   264.4 1175.16   272.21173.457   274.2 1173.02
   283.9 1172.33   293.7 1173.43   303.5 1176.36   313.3 1179.85   323.1 1183.86
   332.9 1188.57   342.7 1193.39   352.5 1198.35   362.3 1203.93   372.1 1210.08
   381.8 1216.83   391.6 1223.82   401.4 1230.96   411.2 1237.85
#Mann= 3 , 0 , 0
       0     .08       0   272.2    .045       0   293.7      .1       0
#XS Ineff= 2 , 0
           80.08 1190.52
Permanent Ineff=
       F       F
Bank Sta=272.2,293.7
XS Rating Curve= 0 ,0
Exp/Cntr=0.3,0.1

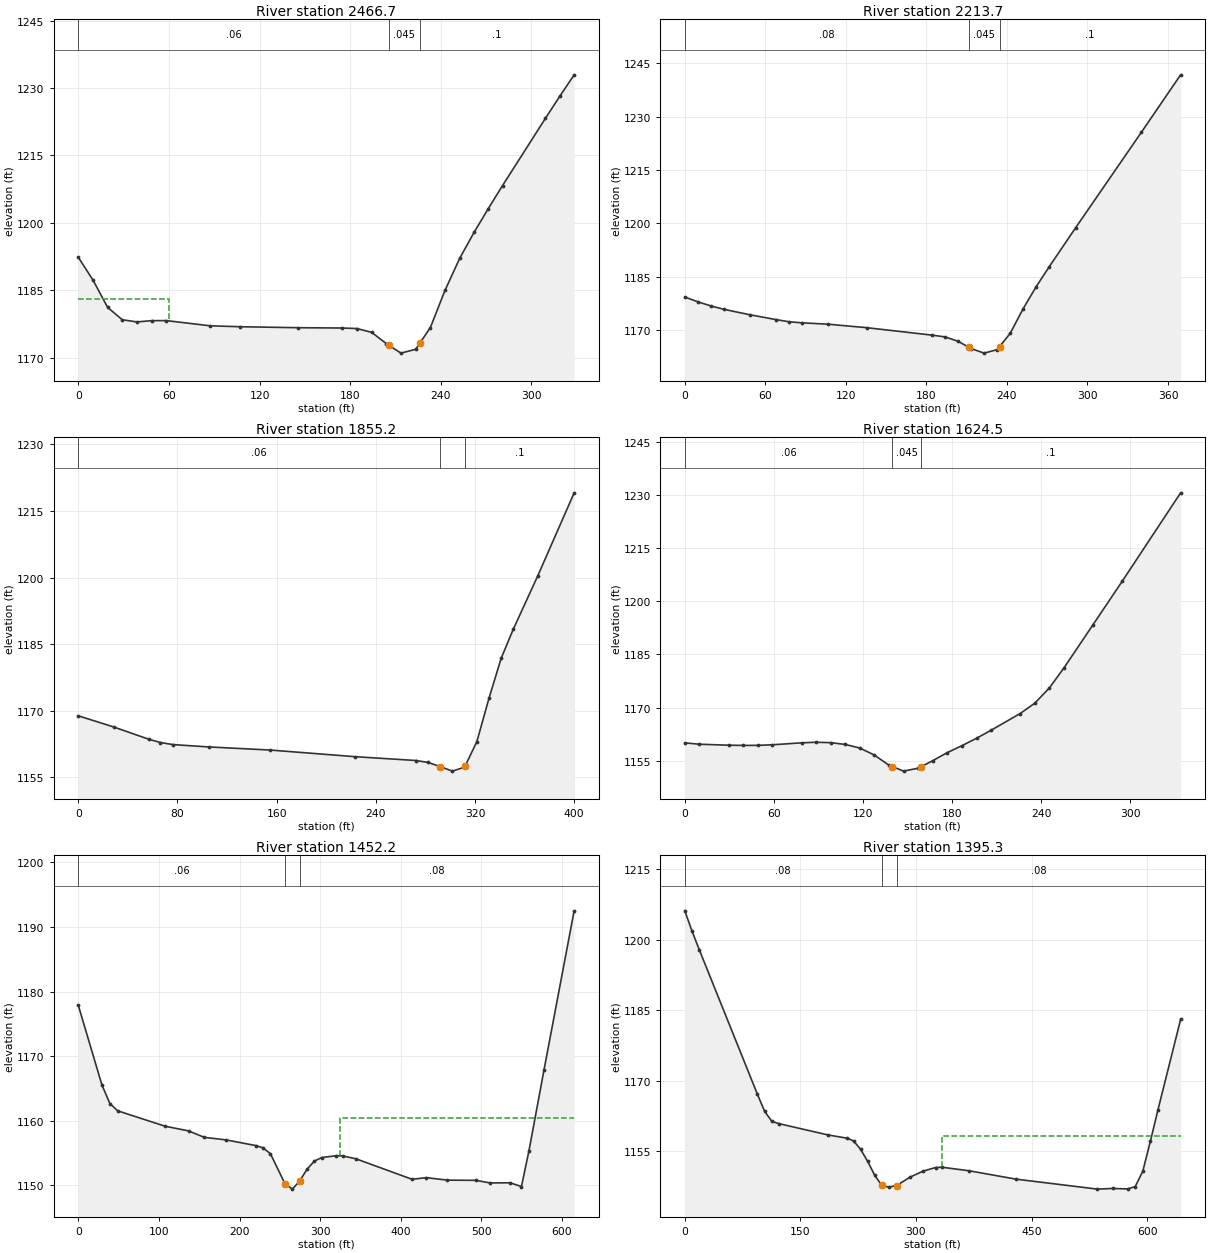
Type RM Length L Ch R = 1 ,2466.7  ,271.7,253,233.5
XS GIS Cut Line= 3
     1849673.633      370436.397     1849507.039      370626.112
     1849467.359      370690.706
#Sta/Elev= 27
       0 1192.32     9.7 1187.26    19.4 1181.18    29.1 1178.42    38.8 1177.94
    48.6 1178.22    58.3 1178.23    87.4 1177.07   106.8 1176.87   145.7 1176.65
   174.8 1176.58   184.5 1176.46   194.2 1175.62   203.9 1173.12   205.41172.792
   213.6 1170.99   223.4 1171.85     2261173.147   233.1 1176.69   242.8 1184.98
   252.5 1192.09     262 1197.86   271.4 1203.15   280.9 1208.31   309.3 1223.28
   318.8  1228.2   328.3 1232.96
#Mann= 3 , 0 , 0
       0     .06       0   205.4    .045       0     226      .1       0
#XS Ineff= 2 , 0
       0      60    1183               0
Permanent Ineff=
       F       F
Bank Sta=205.4,226
XS Rating Curve= 0 ,0
Exp/Cntr=0.3,0.1

Type RM Length L Ch R = 1 ,2213.7  ,356.5,358.5,360.2
XS GIS Cut Line= 3
     1849271.618      370342.178     1849302.171      370602.164
     1849325.822      370707.207
#Sta/Elev= 25
       0 1179.38     9.7 1178.02    19.4 1176.88    29.1 1175.92    48.5 1174.39
    67.9 1173.04    77.6 1172.43    87.3 1172.13   106.6 1171.75   135.7 1170.76
   184.2 1168.68   193.9 1168.18   203.6 1166.96   211.5 1165.29   213.3 1164.91
     223 1163.63   232.7  1164.6   234.51165.446   242.4 1169.16   252.1  1176.1
   261.8 1182.28   271.6 1187.92   291.1 1198.76   340.1 1225.55   369.4  1241.7
#Mann= 3 , 0 , 0
       0     .08       0   211.5    .045       0   234.5      .1       0
Bank Sta=211.5,234.5
XS Rating Curve= 0 ,0
Exp/Cntr=0.3,0.1

Type RM Length L Ch R = 1 ,1855.2  ,221.5,230.7,238.4
XS GIS Cut Line= 3
      1848960.25      370343.384     1848941.293      370406.801
     1848954.872      370740.352
#Sta/Elev= 20
       0 1168.87    28.4 1166.37    56.7 1163.61    66.2 1162.86      76  1162.4
   105.5 1161.86   154.6 1161.17   223.3 1159.67   272.4 1158.81   282.2 1158.37
     292 1157.43   301.8 1156.42   311.6 1157.32     3121157.551   321.5 1163.05
   331.3 1172.83   341.1  1181.8   350.9 1188.37   370.6 1200.35     400 1219.06
#Mann= 3 , 0 , 0
       0     .06       0     292    .045       0     312      .1       0
Bank Sta=292,312
XS Rating Curve= 0 ,0
Exp/Cntr=0.3,0.1

Type RM Length L Ch R = 1 ,1624.5  ,156.6,172.2,187.3
XS GIS Cut Line= 2
     1848801.352      370402.867     1848691.908      370718.244
#Sta/Elev= 29
       0    1160     9.8 1159.62    29.5 1159.34    39.3 1159.28    49.1  1159.3
    58.9 1159.46    78.6 1160.01    88.4 1160.18    98.2 1160.06     108 1159.56
   117.8 1158.54   127.6 1156.56   137.5 1153.67   139.81153.281   147.3 1152.01
   157.1 1152.84   159.31153.316   166.9 1154.96   176.7 1157.24   186.6 1159.22
   196.4  1161.3   206.2 1163.57   225.8  1168.3   235.6 1171.22   245.5 1175.56
   255.3 1181.23   274.9 1193.46   294.6 1205.78   333.8 1230.71
#Mann= 3 , 0 , 0
       0     .06       0   139.8    .045       0   159.3      .1       0
Bank Sta=139.8,159.3
XS Rating Curve= 0 ,0
Exp/Cntr=0.3,0.1

Type RM Length L Ch R = 1 ,1452.2  ,57,57,57.2
XS GIS Cut Line= 6
     1848692.255      370295.096      1848701.49      370451.061
     1848620.952      370465.996     1848480.068      370537.029
     1848330.332      370568.406     1848349.436      370630.925
#Sta/Elev= 30
       0 1177.85    29.3 1165.52    39.1 1162.66    48.8 1161.53   107.4 1159.15
   136.7 1158.42   156.2 1157.42   183.5 1157.02     220 1156.15     229  1155.8
   238.2  1154.9   256.4 1150.23   265.5  1149.4   274.6 1150.66   283.7 1152.47
   292.8 1153.74   301.9 1154.29   320.1 1154.58   328.2 1154.54   344.5 1154.09
   414.1 1150.92   431.6 1151.18   457.8 1150.79   493.2 1150.76   510.9 1150.36
   535.7 1150.38   549.7  1149.8     559 1155.32   577.7 1167.86   615.1  1192.5
#Mann= 3 , 0 , 0
       0     .06       0   256.4    .045       0   274.6     .08       0
#XS Ineff= 2 , 0
                          324.85         1160.42
Permanent Ineff=
       F       F
Bank Sta=256.4,274.6
XS Rating Curve= 0 ,0
Exp/Cntr=0.3,0.1

Type RM Length L Ch R = 1 ,1395.3  ,333.3,310.7,286.6
XS GIS Cut Line= 6
     1848640.356      370231.548     1848647.653      370400.872
      1848599.59      370413.376     1848458.706      370484.408
     1848304.281      370517.175     1848338.148      370619.637
#Sta/Elev= 30
       0 1206.14     9.4 1201.81    18.8 1197.86    94.2 1167.14   103.6 1163.47
     113 1161.36   122.4 1160.86     186 1158.46   210.9 1157.77   219.1 1157.18
   228.2  1155.4   237.4 1152.82   246.5 1149.88   255.6 1147.74   264.7 1147.37
     2751147.705     292 1149.46   309.2 1150.76   325.5 1151.54   333.6  1151.6
   368.8 1150.85     430 1149.06   535.6 1146.94   555.2 1147.08   574.8 1146.98
   584.6 1147.49   594.4 1150.75   604.3 1157.16   614.1 1163.82   643.5 1183.04
#Mann= 3 , 0 , 0
       0     .08       0   255.6    .045       0     275     .08       0
#XS Ineff= 2 , 0
                          334.19         1158.32
Permanent Ineff=
       F       F
Bank Sta=255.6,275
XS Rating Curve= 0 ,0
Exp/Cntr=0.3,0.1

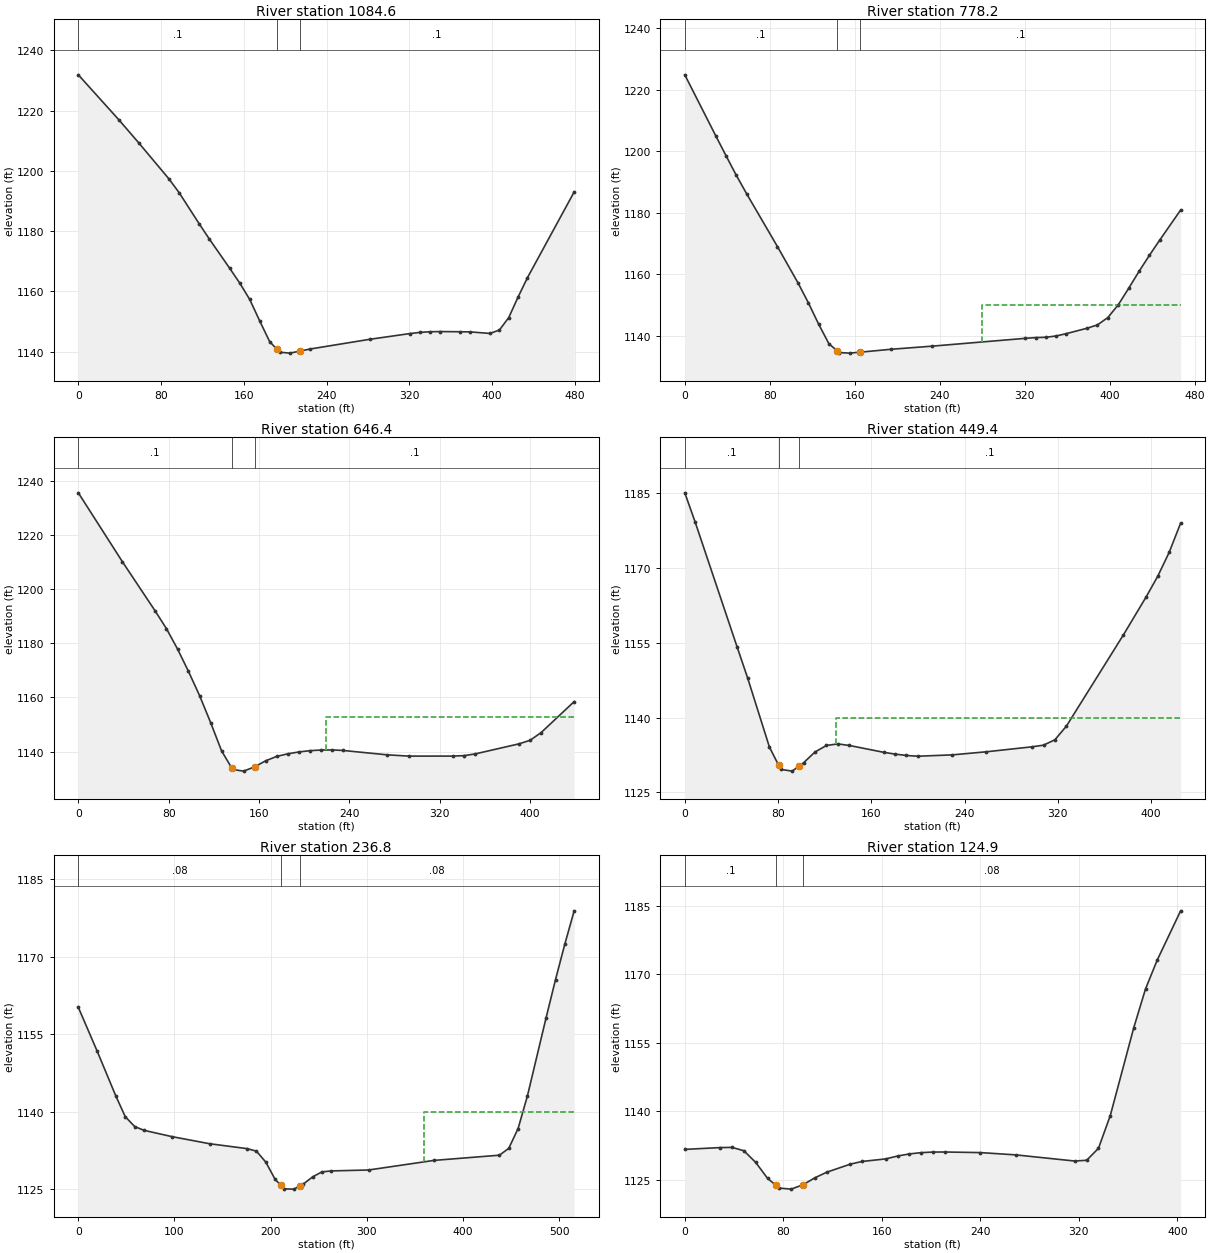
Type RM Length L Ch R = 1 ,1084.6  ,316.3,306.4,296.1
XS GIS Cut Line= 4
     1848259.123      370171.581     1848295.183      370323.217
     1848295.525      370565.293     1848324.255      370641.345
#Sta/Elev= 30
       0 1231.83      39 1216.98    58.4 1209.27    87.7 1197.27    97.4 1192.77
   116.9 1182.39   126.6 1177.39   146.1 1167.78   155.9 1162.83   165.6 1157.38
   175.2  1150.3   184.9 1143.38   191.8 1140.88   194.6 1139.86   204.3 1139.55
     214  1140.2   223.6 1140.89   281.7 1144.14   320.5 1146.04   330.2 1146.42
   339.8 1146.64   349.5  1146.7   368.9 1146.64   378.6 1146.59   397.9 1146.08
     407 1147.22     416 1151.35     425 1158.15   434.1 1164.59   479.2 1192.99
#Mann= 3 , 0 , 0
       0      .1       0   191.8    .045       0     214      .1       0
Bank Sta=191.8,214
XS Rating Curve= 0 ,0
Exp/Cntr=0.3,0.1

Type RM Length L Ch R = 1 ,778.2   ,134.9,131.8,128.2
XS GIS Cut Line= 4
     1847933.712      370331.071      1847998.37      370427.679
     1848116.067      370673.189     1848159.485      370738.313
#Sta/Elev= 30
       0 1224.91    29.1  1205.1    38.8  1198.6    48.4 1192.28    58.1 1186.28
    87.2 1169.04   106.6 1157.21   116.2 1150.83     126  1143.8   135.7  1137.4
   143.4 1135.14   145.4 1134.55   155.1 1134.36   164.9 1134.66     194 1135.61
   232.9 1136.63   320.4 1139.17   330.2 1139.41   339.9 1139.52   349.6 1139.94
   359.3 1140.71   378.8 1142.47   388.5 1143.54   398.3 1145.94   408.1 1150.09
   417.9 1155.45   427.6 1160.93   437.4 1166.18   447.2 1171.17   466.8 1180.92
#Mann= 3 , 0 , 0
       0      .1       0   143.4    .045       0   164.9      .1       0
#XS Ineff= 2 , 0
       0                     280       0    1150
Permanent Ineff=
       F       F
Bank Sta=143.4,164.9
XS Rating Curve= 0 ,0
Exp/Cntr=0.3,0.1

Type RM Length L Ch R = 1 ,646.4   ,192.5,197,201
XS GIS Cut Line= 2
     1847815.531      370397.995     1848061.557      370761.987
#Sta/Elev= 30
       0 1235.49      39  1210.1    68.3 1191.76    78.1 1185.35    87.9 1177.86
    97.6 1169.59   107.4 1160.69   117.2 1150.74   126.9 1140.29     1361133.901
   136.7 1133.41   146.4  1132.8   156.2 1134.38     166 1136.62   175.7 1138.22
   185.5 1139.18   195.3 1139.87     205 1140.34   214.8 1140.58   224.6 1140.62
   234.3 1140.44   273.4 1138.82   292.9 1138.34     332 1138.35   341.7 1138.52
   351.5 1139.14   390.5 1142.87   400.3 1144.19     410 1147.01   439.3 1158.46
#Mann= 3 , 0 , 0
       0      .1       0     136    .045       0   156.2      .1       0
#XS Ineff= 2 , 0
                           219.2         1152.67
Permanent Ineff=
       F       F
Bank Sta=136,156.2
XS Rating Curve= 0 ,0
Exp/Cntr=0.3,0.1

Type RM Length L Ch R = 1 ,449.4   ,212.7,212.6,211.7
XS GIS Cut Line= 3
     1847717.303      370532.311      1847719.03      370595.034
     1847862.376      370928.048
#Sta/Elev= 29
       0 1185.09       9 1179.15    44.8 1154.22    53.8 1148.02    72.6 1134.08
    80.6 1130.39    82.3 1129.61    92.1 1129.26      981130.271   101.9 1130.94
   111.7  1133.1   121.5 1134.41   131.3 1134.72   141.1 1134.41   170.5 1133.04
   180.3 1132.68   190.1  1132.4   199.9 1132.25   229.3 1132.52   258.7 1133.14
   297.9 1134.14   307.7 1134.47   317.5 1135.56   327.3 1138.28   376.3 1156.62
   395.9 1164.28   405.7 1168.37   415.5 1173.16   425.3 1179.01
#Mann= 3 , 0 , 0
       0      .1       0    80.6    .045       0      98      .1       0
#XS Ineff= 2 , 0
       0                     130       0    1140
Permanent Ineff=
       F       F
Bank Sta=80.6,98
XS Rating Curve= 0 ,0
Exp/Cntr=0.3,0.1

Type RM Length L Ch R = 1 ,236.8   ,112.6,112,111.6
XS GIS Cut Line= 3
     1847634.801      370561.471     1847534.782      370681.377
      1847684.47      371008.284
#Sta/Elev= 30
       0 1160.19    19.5 1151.74      39 1143.01    48.8    1139    58.6 1137.09
    68.3 1136.35    97.6 1135.12   136.6 1133.75   175.6  1132.8   185.3 1132.31
     195 1130.18   204.7 1126.84   210.8 1125.68   214.4    1125   224.2 1124.95
   230.8 1125.61   233.9 1125.92   243.6 1127.31   253.3 1128.29     263 1128.48
   301.9 1128.66   369.9 1130.52     438 1131.53   447.7 1132.86   457.4  1136.7
   467.1 1143.03   486.5 1158.16   496.3 1165.57     506 1172.46   515.7 1178.91
#Mann= 3 , 0 , 0
       0     .08       0   210.8    .045       0   230.8     .08       0
#XS Ineff= 2 , 0
       0                     360       0    1140
Permanent Ineff=
       F       F
Bank Sta=210.8,230.8
XS Rating Curve= 0 ,0
Exp/Cntr=0.3,0.1

Type RM Length L Ch R = 1 ,124.9   ,98.6,106.2,112.4
XS GIS Cut Line= 3
     1847428.749       370720.67      1847579.99      371031.334
     1847621.179      371070.887
#Sta/Elev= 30
       0 1131.62    28.8 1132.02    38.4 1132.06      48 1131.32    57.6 1128.76
    67.2 1125.28      74 1123.76    76.8 1123.14    86.4 1122.92      96 1123.88
   105.6 1125.39   115.2 1126.62   134.4 1128.39     144 1128.98   163.2 1129.54
   172.8 1130.17   182.4 1130.63     192 1130.91   201.6 1131.04   211.2 1131.05
     240 1130.92   268.7 1130.42   316.7 1129.07   326.3 1129.24   335.9 1131.86
   345.5 1139.04   364.6 1158.31   374.1 1166.76   383.6 1173.08   402.6 1183.86
#Mann= 3 , 0 , 0
       0      .1       0      74    .045       0      96     .08       0
Bank Sta=74,96
XS Rating Curve= 0 ,0
Exp/Cntr=0.3,0.1

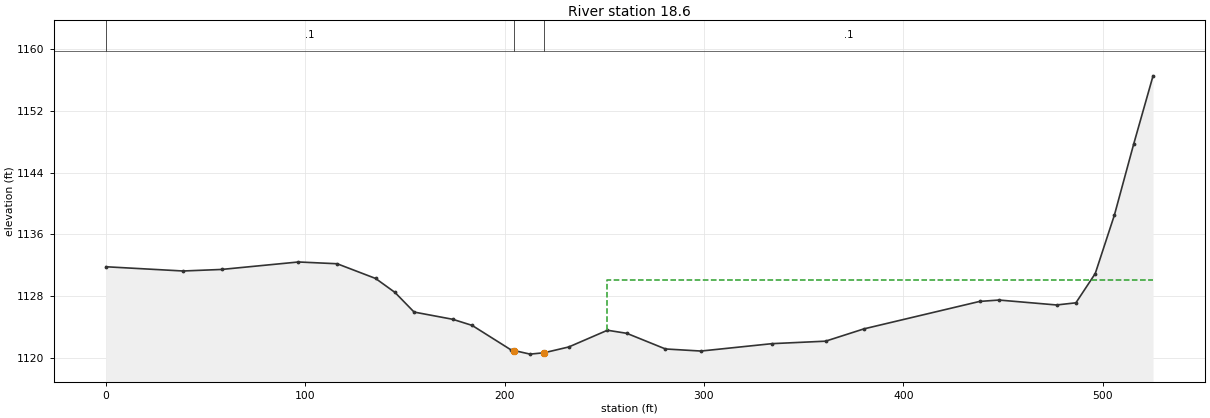
Type RM Length L Ch R = 1 ,18.6    ,26.7,18.6,11.2
XS GIS Cut Line= 5
     1847437.102      370663.215     1847371.912       370803.45
     1847393.623      370927.621     1847415.332      371004.901
     1847546.451      371103.889
#Sta/Elev= 30
       0 1131.78    38.7 1131.23      58 1131.43    96.6  1132.4     116 1132.17
   135.3 1130.26     145 1128.45   154.6  1125.9     174 1124.96   183.7 1124.17
   203.1 1121.01   204.9  1120.9   212.8 1120.44   219.9 1120.62   232.2 1121.37
   251.6 1123.54   261.3 1123.14   280.7 1121.11   298.5 1120.84   334.2  1121.8
     361 1122.12   380.3 1123.72   438.3 1127.28     448 1127.46   476.9 1126.82
   486.6  1127.1   496.3  1130.9   505.9 1138.48   515.6 1147.72   525.3 1156.56
#Mann= 3 , 0 , 0
       0      .1       0   204.9    .045       0   219.9      .1       0
#XS Ineff= 2 , 0
       0                   251.6       0    1130
Permanent Ineff=
       F       F
Bank Sta=204.9,219.9
XS Rating Curve= 0 ,0
Exp/Cntr=0.3,0.1

Chan Stop Cuts=-1
Use User Specified Reach Order=0
Composite Channel Slope=5